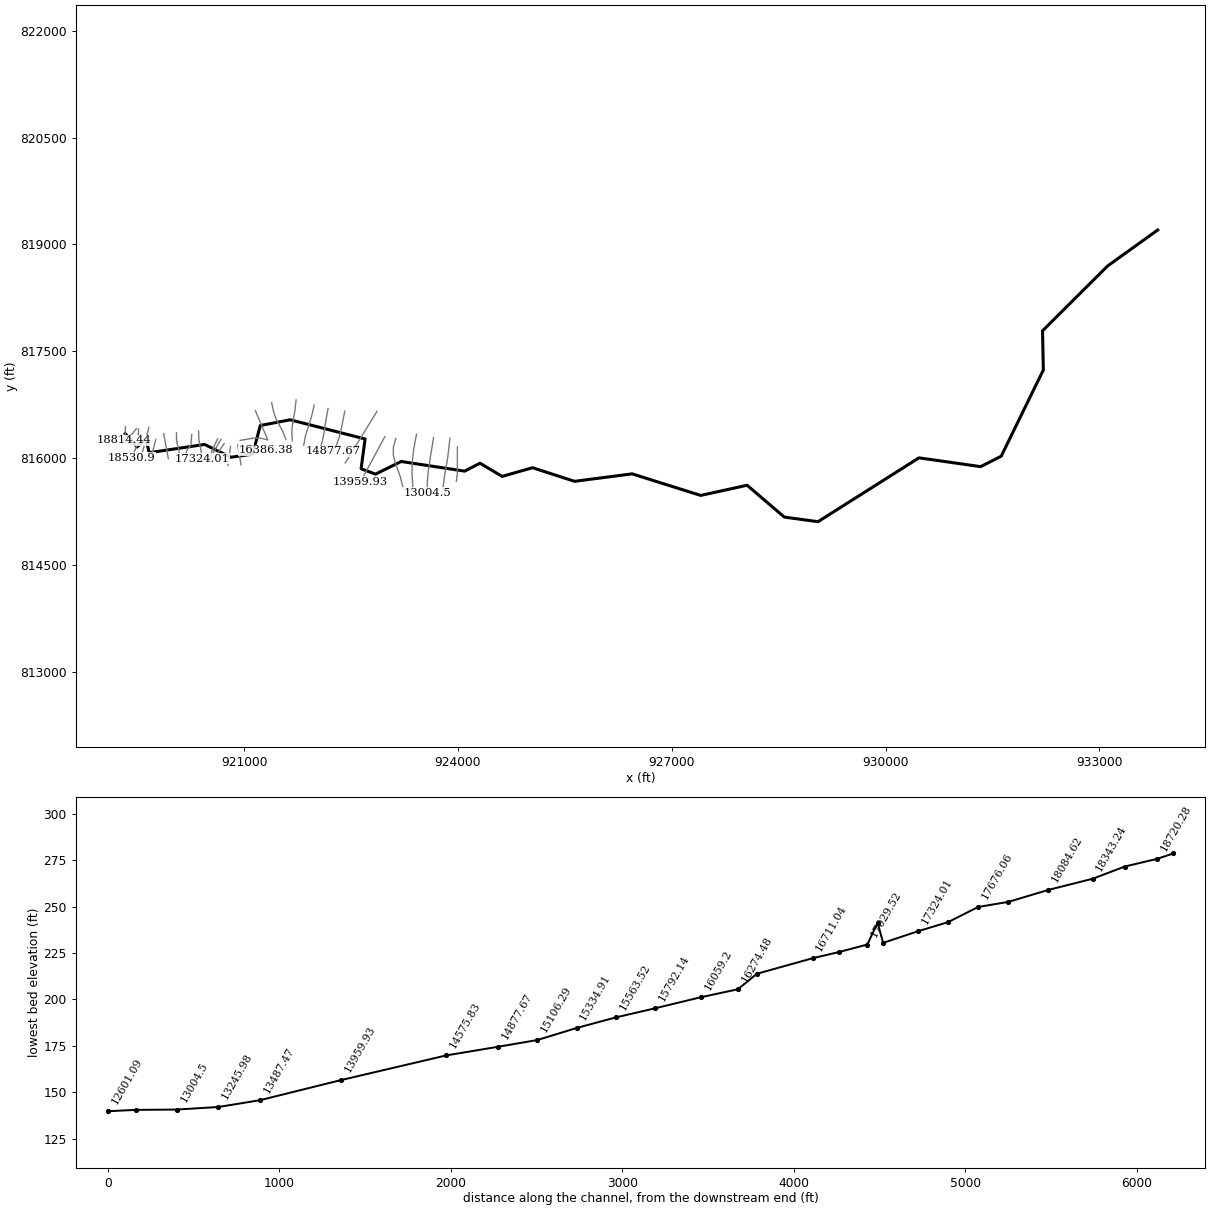
--- 15896_ras.prj (project) ---

Proj Title=15896
Current Plan=p01
Default Exp/Contr=0.3,0.1
English Units
Geom File=g01
Flow File=f01
Plan File=p01
Y Axis Title=Elevation
X Axis Title(PF)=Main Channel Distance
X Axis Title(XS)=Station
BEGIN DESCRIPTION:
RFD model 15896 exported to HEC-RAS
END DESCRIPTION:

--- 15896_ras.p01 (plan) ---

Plan Title=Plan 01
Program Version=4.10
Short Identifier=Plan 01
Geom File=g01
Flow File=f01
Subcritical Flow
Calc Critical at every XS
Secant Critical Depth

--- 15896_ras.f01 (steady flow) ---

Flow Title=Flow 01
Program Version=5.01
Number of Profiles= 6
Profile Names=10yr,25yr,50yr,100yr,100plus,500yr
River Rch & RM=15896,72,18814.44
  236.83  347.52  443.47  520.63  760.12 1151.94
River Rch & RM=15896,72,18720.28
  240.13  352.41  449.77  528.06  770.97 1166.25
River Rch & RM=15896,72, 18530.9
  248.11  364.34  465.19  546.36  797.68 1201.72
River Rch & RM=15896,72,18084.62
   255.2  375.07  479.17  563.04  822.04 1234.46
River Rch & RM=15896,72,17852.08
  414.78  612.37  784.98  924.54 1349.83 1898.75
River Rch & RM=15896,72,17676.06
  501.08  743.41  956.15 1129.29 1648.77 2268.21
River Rch & RM=15896,72,17500.04
   537.2  798.09 1027.48 1214.47 1773.12 2418.34
River Rch & RM=15896,72,17324.01
  539.78     802 1032.58 1220.57 1782.03 2429.05
River Rch & RM=15896,72,17121.84
  714.01 1068.42 1382.33 1640.59 2395.25 3158.72
River Rch & RM=15896,72, 17089.7
  715.63 1070.87 1385.53 1644.41 2400.84 3165.16
River Rch & RM=15896,72,16866.01
  724.76 1084.78 1403.74 1666.24  2432.7 3202.04
River Rch & RM=15896,72,16711.04
  726.59 1087.64 1407.53 1670.83 2439.42 3210.03
River Rch & RM=15896,72,16386.38
  750.03 1124.43 1456.62 1730.63 2526.72 3314.86
River Rch & RM=15896,72,16274.48
  755.36 1132.61  1467.4 1743.62 2545.68 3336.92
River Rch & RM=15896,72, 16059.2
  792.85 1190.68 1544.28 1836.61 2681.45 3496.01
River Rch & RM=15896,72,15792.14
  798.46 1199.47    1556 1850.88 2702.29 3520.71
River Rch & RM=15896,72,15563.52
  829.63 1248.42 1621.36 1930.54 2818.58 3658.39
River Rch & RM=15896,72,15334.91
  840.38 1265.27 1643.82 1957.89 2858.51 3705.34
River Rch & RM=15896,72,15106.29
   844.2 1271.24 1651.79 1967.58 2872.66 3721.94
River Rch & RM=15896,72,14877.67
  850.39 1280.96 1664.75 1983.38 2895.73 3749.05
River Rch & RM=15896,72,14575.83
  920.35 1391.88 1813.75 2165.92 3162.24 4064.24
River Rch & RM=15896,72,13959.93
  1006.1 1528.18 1997.18 2391.02 3490.88 4449.12
River Rch & RM=15896,72,13487.47
 1017.83 1547.23 2023.15 2423.24 3537.93 4505.22
River Rch & RM=15896,72,13245.98
 1130.01 1727.87 2268.24 2726.16  3980.2 5022.67
River Rch & RM=15896,72, 13004.5
 1144.85 1751.94 2301.05 2766.87 4039.63 5092.19
River Rch & RM=15896,72,12763.01
 1152.46 1764.33 2317.95 2787.88 4070.31 5128.15
River Rch & RM=15896,72,12601.09
 1180.58 1810.87 2382.16 2868.38 4187.83 5268.35
River Rch & RM=15896,72,12280.04
  1189.9 1826.26 2403.37 2894.93 4226.59 5314.32
River Rch & RM=15896,72,12038.55
 1223.87 1882.44 2480.84 2992.04 4368.38 5482.43
River Rch & RM=15896,72,11797.07
 1226.33 1886.59 2486.64 2999.38 4379.09 5495.38
River Rch & RM=15896,72,11555.58
 1261.97 1946.13 2569.24 3103.45 4531.03 5676.68
River Rch & RM=15896,72, 11314.1
 1264.43 1950.26    2575 3110.73 4541.67 5689.45
River Rch & RM=15896,72,11072.61
 1318.41  2042.4 2704.43 3275.52 4782.26 5981.42
River Rch & RM=15896,72,10831.12
 1327.12 2057.84 2726.57 3304.19 4824.12 6033.91
River Rch & RM=15896,72,10589.64
  1353.5 2102.56 2789.17 3383.68 4940.17 6172.99
River Rch & RM=15896,72,10348.15
 1363.62 2120.46 2814.83 3416.89 4988.66 6233.46
River Rch & RM=15896,72,10106.67
  1370.2  2132.1 2831.53 3438.51 5020.23 6272.82
River Rch & RM=15896,72, 9865.18
 1544.17 2423.13  3236.1 3949.33 5766.03 7142.91
River Rch & RM=15896,72,9623.694
 1592.96 2509.24 3359.56 4109.28 5999.55 7427.88
River Rch & RM=15896,72,9382.208
 1596.82 2516.09 3369.43 4122.12 6018.29 7450.86
River Rch & RM=15896,72,9217.517
 1603.47 2528.21  3387.1 4145.33 6052.19  7493.3
River Rch & RM=15896,72,8961.699
 1609.02 2538.45 3402.13 4165.17 6081.15 7529.93
River Rch & RM=15896,72,8736.424
  1662.5 2635.93 3544.39 4352.21 6354.23 7871.12
River Rch & RM=15896,72,8486.913
 1666.81 2643.73 3555.74  4367.1 6375.97 7898.07
River Rch & RM=15896,72,8237.402
 1677.07  2662.5 3583.21 4403.31 6428.83 7964.17
River Rch & RM=15896,72,7987.891
 1686.45 2679.88 3608.82 4437.23 6478.35 8026.72
River Rch & RM=15896,72, 7738.38
 1690.76 2688.02  3620.9 4453.34 6501.87 8056.81
River Rch & RM=15896,72,7488.869
 1695.29 2696.62 3633.73 4470.51 6526.94 8089.07
River Rch & RM=15896,72,7239.358
 1699.37 2704.35 3645.26 4485.91 6549.44 8117.96
River Rch & RM=15896,72,6989.847
 1702.52 2710.43 3654.39  4498.2 6567.37 8141.26
River Rch & RM=15896,72,6740.336
 1708.41 2721.75 3671.37 4521.02 6600.69 8184.47
River Rch & RM=15896,72,6490.825
 1716.66  2737.4 3694.71 4552.25 6646.29 8243.04
River Rch & RM=15896,72,6241.315
 1718.51 2740.92 3699.97  4559.3 6656.58 8256.28
River Rch & RM=15896,72,5991.804
 1737.03 2776.22 3752.75 4630.06 6759.89 8389.31
River Rch & RM=15896,72,5742.293
 1742.15 2786.35 3768.19 4651.05 6790.53 8429.82
River Rch & RM=15896,72,5492.782
 1744.22 2790.45 3774.43 4659.55 6802.94 8446.22
River Rch & RM=15896,72,5243.271
 1818.71 2931.37 3984.49 4940.69 7213.41 8970.06
River Rch & RM=15896,72,5048.289
 1823.18 2940.09 3997.71 4958.61 7239.57  9004.2
River Rch & RM=15896,72,4853.307
 1826.07 2945.76 4006.33 4970.32 7256.66 9026.57
River Rch & RM=15896,72,4633.057
 1833.39  2960.2 4028.33 5000.27 7300.39    9084
River Rch & RM=15896,72,4528.479
 1836.16 2965.62 4036.55 5011.42 7316.67 9105.24
River Rch & RM=15896,72,4085.088
 1843.38 2980.03 4058.62  5041.6 7360.73 9163.54
River Rch & RM=15896,72,3509.878
 1854.15 3001.59 4091.71  5086.9 7426.87 9251.24
River Rch & RM=15896,72,2970.101
 1857.37 3008.05 4101.63  5100.5 7446.73 9277.59
River Rch & RM=15896,72,2111.154
 1865.64 3024.51 4126.82 5134.91 7496.96 9343.87
River Rch & RM=15896,72,2008.426
 1866.82 3026.86 4130.41 5139.82 7504.14 9353.32
River Rch & RM=15896,72,1284.759
  1962.8  3212.6 4411.12 5519.98 8059.1710069.42
River Rch & RM=15896,72,       0
 1989.53 3264.02 4488.67 5624.91 8212.3710265.56
Boundary for River Rch & Prof#=15896,72,1
Up Type= 0
Dn Type= 2
Boundary for River Rch & Prof#=15896,72,2
Up Type= 0
Dn Type= 2
Boundary for River Rch & Prof#=15896,72,2
Up Type= 0
Dn Type= 2
Boundary for River Rch & Prof#=15896,72,2
Up Type= 0
Dn Type= 2
Boundary for River Rch & Prof#=15896,72,2
Up Type= 0
Dn Type= 2
Boundary for River Rch & Prof#=15896,72,2
Up Type= 0
Dn Type= 2

--- 15896_ras.g01 (geometry) ---

Geom Title=15896
Program Version=4.10

River Reach=15896,72
Reach XY= 30
 919330.09909481816346.133548429919496.765761467816157.591881778
 919620.72409481816271.133548434 919667.59909481  816078.4252151
 920444.50881705816194.050215102920812.627398522816014.460064733
921119.886861922816058.398559128 921225.84562257816459.762020657
921645.924705149816540.102736323922696.559985612816270.851442919
922640.521969618815853.994458383 922842.09944564815777.439861705
923202.890835258815955.142664147924093.684164259815819.571048449
924308.523193837815930.884345934924619.867511276  815745.9627965
925045.740241887815867.683113054925635.338496568815676.786440691
926442.654988944815781.500144625927405.316108706815478.859242891
928056.483861239815621.565868261928578.447664799815175.071622248
929051.412096738815110.390102339930467.765931429816006.137674525
931332.834969045815882.932941337931621.595867425816029.000052332
  932212.7524513817238.841881751932201.901756855817788.972090102
933115.530229033 818699.34535398933817.318254439819202.789915154

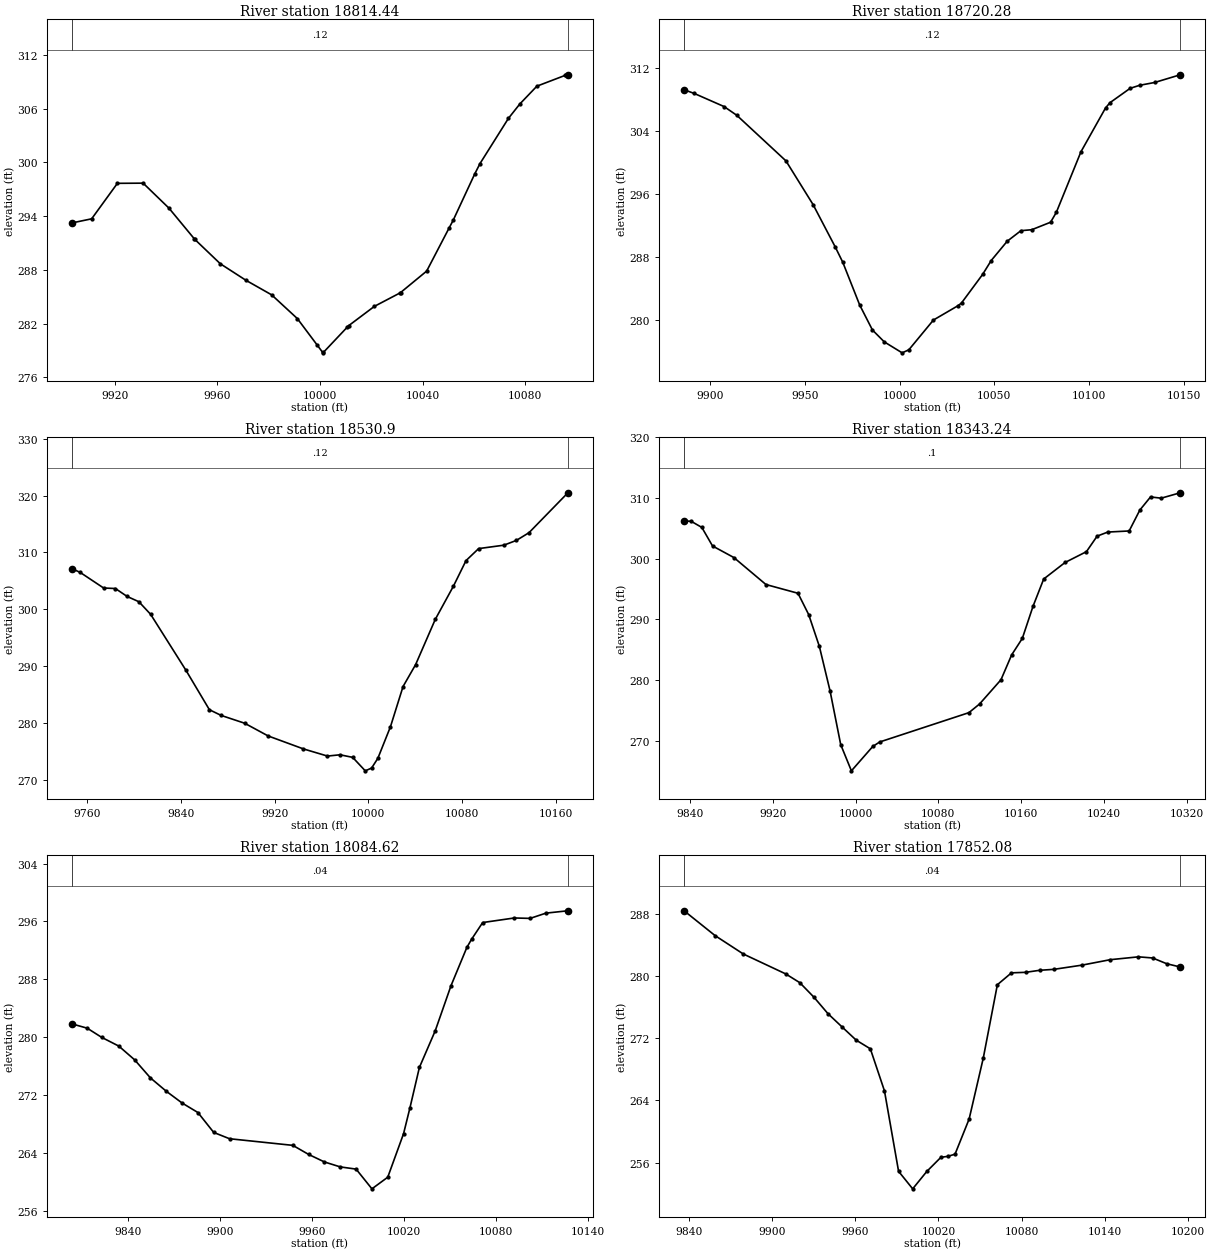
Type RM Length L Ch R = 1 ,18814.44,94.165500,94.165500,94.165500
XS GIS Cut Line= 6
919334.133444139816442.718694425919330.693057548816395.151589481
919331.301855932816335.482579956 919329.71116866816314.813016348
919322.529643418816286.884488635 919306.97008741816254.073937275
#Sta/Elev= 29
9903.335293.24139911.074293.7043  9921.1297.66619931.126297.68639941.153294.9046
9951.027291.48069951.178291.42749961.179288.68649971.179286.83719981.179285.2138
9991.179282.5671    9999 279.575   10001278.806710001.18278.7374 10010.7281.6266
10011.18281.770110021.21283.928810031.24 285.43510031.43285.475410041.56287.8666
10050.35292.705710051.89293.541710060.27298.706410062.35299.879710073.42304.9266
10077.84306.523910084.49308.515510095.56309.729210096.58309.7888
#Mann= 3 , 0 , 0
9903.335    0.12       09903.335    0.12       010096.58    0.12       0
#XS Ineff= 2 , 0
       0                               0
Bank Sta=9903.335,10096.58
Exp/Cntr=0.3,0.1

Type RM Length L Ch R = 1 ,18720.28,189.383300,189.383300,189.383300
XS GIS Cut Line= 2
919488.442634376816416.435072727919321.341939932 816214.61215606
#Sta/Elev= 30
9886.213309.22739891.611308.75319907.292307.09589914.042305.98399940.007300.1959
9954.333294.64789965.972289.30079970.013287.32899978.955281.89819985.694 278.721
9991.938277.217810001.37275.824910004.92276.2117 10017.9279.990110030.89281.8106
10032.74282.159810043.87285.777610048.42 287.54610056.85289.9919 10064.1 291.332
10069.83291.456410079.78292.407310082.82293.6677 10095.8301.346310108.78306.9089
10111.14307.584210121.77309.404110126.82309.791710134.75310.150110148.23311.1267
#Mann= 3 , 0 , 0
9886.213    0.12       09886.213    0.12       010148.23    0.12       0
#XS Ineff= 2 , 0
       0                               0
Bank Sta=9886.213,10148.23
Exp/Cntr=0.3,0.1

Type RM Length L Ch R = 1 , 18530.9,187.655600,187.655600,187.655600
XS GIS Cut Line= 3
919518.824578821816412.094794949 919501.46346771816201.591322727
 919423.33846771816004.108683838
#Sta/Elev= 30
9746.848307.17089753.967306.50899774.035303.76339784.069303.67399794.103302.2819
9804.137301.35419814.171299.14279844.273289.33399864.341282.39759874.375281.3969
9894.443280.02519914.511277.79079944.612275.51719965.155  274.269975.909 274.485
9986.663 274.0339997.417271.666910002.82272.155610008.17273.864710018.93279.4117
10029.68286.467810040.43290.324810057.19298.2581 10072.7304.094610083.45308.5756
 10094.2310.681810115.71  311.2810126.47312.122610137.22313.475310170.44320.4819
#Mann= 3 , 0 , 0
9746.848    0.12       09746.848    0.12       010170.44    0.12       0
#XS Ineff= 2 , 0
       0                               0
Bank Sta=9746.848,10170.44
Exp/Cntr=0.3,0.1

Type RM Length L Ch R = 1 ,18343.24,258.617400,258.617400,258.617400
XS GIS Cut Line= 2
919662.053745487816431.626044949919542.696106598815967.216322727
#Sta/Elev= 30
9834.225306.23329841.066306.17689851.391 305.1659861.716302.11279882.366 300.202
9913.341 295.7599944.316294.32049954.641290.81219964.966285.56949975.291 278.251
9985.616269.38119995.941265.068810016.59269.083810023.26269.820910109.52274.6537
10119.84276.086110140.49280.069710150.82284.168410161.14286.890410171.47292.1727
10181.79296.665810202.44299.390210223.09301.172510233.42303.729510243.74304.4027
10264.39304.582510274.72308.026910285.04310.186410295.37309.983810313.73 310.873
#Mann= 3 , 0 , 0
9834.225     0.1       09834.225     0.1       010313.73     0.1       0
#XS Ineff= 2 , 0
       0                               0
Bank Sta=9834.225,10313.73
Exp/Cntr=0.3,0.1

Type RM Length L Ch R = 1 ,18084.62,232.540300,232.540300,232.540300
XS GIS Cut Line= 2
919759.856062529816264.721497673919679.373123159815951.115561509
#Sta/Elev= 30
9803.365281.84269813.401281.2441  9822.9279.9716 9834.05278.76769844.374276.8688
9854.698274.36849865.022272.52759875.346270.9006 9885.67269.58539895.994266.8326
9906.318265.96279947.614 265.0479957.938263.79269968.262 262.7519978.586262.0683
 9988.91261.76379999.235259.037510009.56260.645210019.88266.663110024.04270.2322
10030.21275.819710040.53280.874210050.85287.121210061.18292.400810064.27293.5335
 10071.5295.842610092.15296.474910102.48296.4173 10112.8297.144710127.13297.4693
#Mann= 3 , 0 , 0
9803.365    0.04       09803.365    0.04       010127.13    0.04       0
#XS Ineff= 2 , 0
       0                               0
Bank Sta=9803.365,10127.13
Exp/Cntr=0.3,0.1

Type RM Length L Ch R = 1 ,17852.08,176.022300,176.022300,176.022300
XS GIS Cut Line= 2
919870.387078821816346.990628282919935.491245487815995.428128282
#Sta/Elev= 30
9836.694288.45529859.059285.25139879.399282.88189909.909280.31969920.079279.1869
9930.249277.31829940.419275.18199950.589273.47149960.759271.77129970.929270.6591
9981.099265.23529991.269254.865810001.44252.605510011.61254.850110021.78256.6705
10026.78256.794910031.95257.072510042.12261.609110052.29269.447210062.46278.9212
10072.63280.4533 10082.8280.520310092.97280.782410103.14280.903310123.48281.4479
10143.82  282.1510164.16282.517410174.33282.3709 10184.5281.628710194.23281.2085
#Mann= 3 , 0 , 0
9836.694    0.04       09836.694    0.04       010194.23    0.04       0
#XS Ineff= 2 , 0
       0                               0
Bank Sta=9836.694,10194.23
Exp/Cntr=0.3,0.1

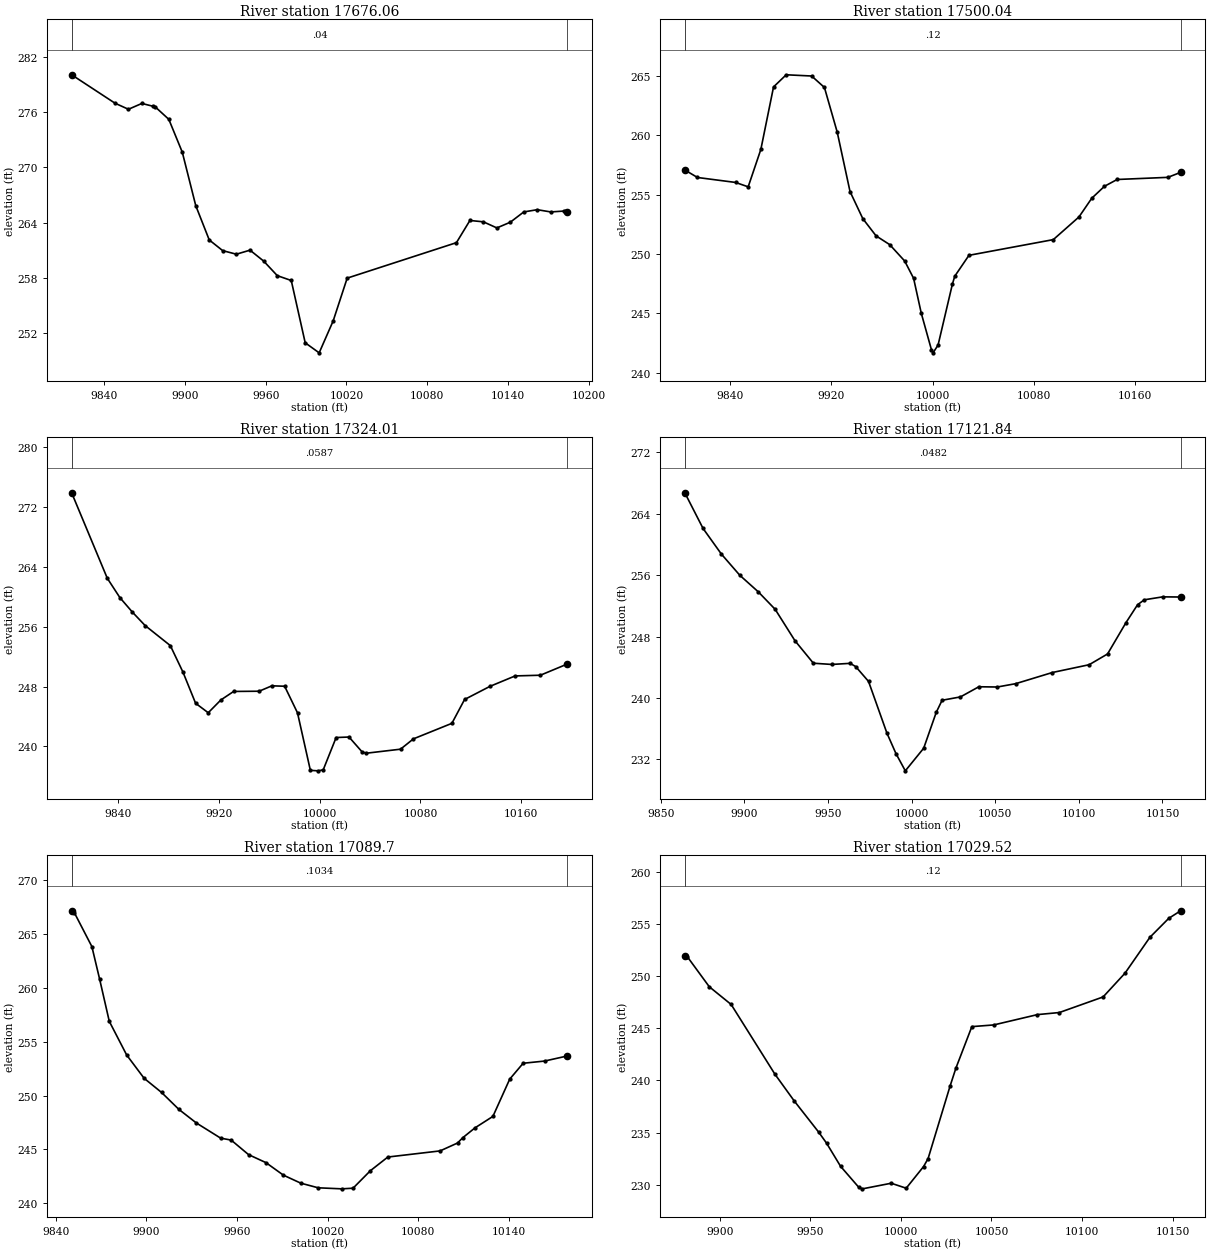
Type RM Length L Ch R = 1 ,17676.06,176.022300,176.022300,176.022300
XS GIS Cut Line= 6
920050.102029478816357.222709798920049.849080335816296.542394734
920053.271018176816245.220042933920060.137509575816205.042932322
920083.790581787816110.360422448920092.218527732815992.586866138
#Sta/Elev= 30
9815.683280.02339847.906276.94189857.906276.28219867.906276.91539876.364276.6018
 9877.91276.53159887.932 275.1929897.954 271.6269907.976265.82479917.999262.1094
9928.023260.94929938.168 260.5659948.313 261.0039958.458259.81769968.604258.2375
9978.974 257.7139989.343250.95669999.726249.867710010.15253.334210020.55257.9697
10101.79261.816910111.82264.224310121.84 264.07510131.85263.414410141.86264.0357
10151.88265.150310161.89 265.39110171.91 265.14910181.92265.245610184.34265.1034
#Mann= 3 , 0 , 0
9815.683    0.04       09815.683    0.04       010184.34    0.04       0
#XS Ineff= 2 , 0
       0                               0
Bank Sta=9815.683,10184.34
Exp/Cntr=0.3,0.1

Type RM Length L Ch R = 1 ,17500.04,176.022300,176.022300,176.022300
XS GIS Cut Line= 6
920264.210820689816334.982785928920252.699110848816194.659966949
920242.116935057 816168.03053977920206.488282944816126.488289198
920189.766749874816093.389764216920172.872188124815964.959882494
#Sta/Elev= 30
9804.223257.08539814.219256.45229844.259256.03469854.272255.66479864.285258.8221
9874.298264.08929884.311265.11319904.392265.00929914.495264.04169924.599260.2738
9934.703255.26689944.806252.97929955.298251.52679966.057250.78869977.869249.4095
9984.913247.94919990.971245.0061    9999241.926310000.27241.664810004.24242.3201
10015.56247.464110017.42248.127110028.63249.888210095.25 251.212 10115.5253.1226
10125.62254.700510135.64255.708410145.66256.283510185.74256.4634 10195.8256.8836
#Mann= 3 , 0 , 0
9804.223    0.12       09804.223    0.12       0 10195.8    0.12       0
#XS Ineff= 2 , 0
       0                               0
Bank Sta=9804.223,10195.8
Exp/Cntr=0.3,0.1

Type RM Length L Ch R = 1 ,17324.01,202.176500,202.176500,202.176500
XS GIS Cut Line= 6
 920360.33053254816383.279551002920363.922816797816266.472248762
920371.616077799816215.910414198920397.373449266816093.469995051
920401.768412259816051.575342202920402.995768572815993.506228183
#Sta/Elev= 30
9803.293273.86859831.573262.45549841.573259.87029851.573257.91959861.573256.1454
9881.595 253.4639891.618249.92289901.641 245.7669911.664244.4986  9921.7246.2085
9931.815247.34349952.045247.3739 9962.16248.09539972.284248.03959982.494244.4859
9992.703236.8082    9999236.743610002.91236.884510013.13241.191110023.36241.2578
10033.58 239.30610036.82239.091710064.24239.634710074.47241.013610104.99 243.087
10115.05246.269910135.16248.020110155.18249.416610175.18249.508810196.68251.0134
#Mann= 3 , 0 , 0
9803.293  0.0587       09803.293  0.0587       010196.68  0.0587       0
#XS Ineff= 2 , 0
       0                               0
Bank Sta=9803.293,10196.68
Exp/Cntr=0.3,0.1

Type RM Length L Ch R = 1 ,17121.84,32.134200,32.134200,32.134200
XS GIS Cut Line= 2
920627.435856866816274.925323795920504.309688329816005.256353442
#Sta/Elev= 30
9864.416266.73099875.327262.0829 9886.32258.73499897.313255.97979908.306253.8334
9918.434 251.5499930.292247.45139941.285244.52519952.278244.36619963.271244.5084
9966.588244.08719974.264242.15549985.257235.42069990.665232.7512 9996.25230.5042
10007.24233.450610014.74 238.12110018.24239.699110029.23240.136510040.22241.4588
10051.22241.425210062.21241.858710084.19 243.31610106.18  244.3310117.17245.7312
10128.17249.808210135.13252.149510139.16252.788310150.15253.171410160.86253.1503
#Mann= 3 , 0 , 0
9864.416  0.0482       09864.416  0.0482       010160.86  0.0482       0
#XS Ineff= 2 , 0
       0                               0
Bank Sta=9864.416,10160.86
Exp/Cntr=0.3,0.1

Type RM Length L Ch R = 1 , 17089.7,60.181100,60.181100,60.181100
XS GIS Cut Line= 2
920674.269123426816266.616195857920510.352690466815981.839720162
#Sta/Elev= 30
9850.431267.16139852.296266.96339863.834263.83779869.012260.79059875.372256.8929
9886.911253.76229898.449251.60269909.987250.29019921.525248.70999933.064247.4525
9949.195246.0411 9956.14245.86299967.678244.51089979.217243.76659990.755242.6048
10002.29241.860110013.83241.429410029.38241.333510036.91241.392210048.45243.0222
10059.98244.2878 10094.6244.856910106.14245.587910109.56 246.07310117.68 246.993
10129.61248.063110140.75251.525110149.65252.998710163.83253.201910179.01253.6788
#Mann= 3 , 0 , 0
9850.431  0.1034       09850.431  0.1034       010179.01  0.1034       0
#XS Ineff= 2 , 0
       0                               0
Bank Sta=9850.431,10179.01
Exp/Cntr=0.3,0.1

Type RM Length L Ch R = 1 ,17029.52,163.510200,163.510200,163.510200
XS GIS Cut Line= 2
920718.836264184816206.186174489920565.495084964815979.573594361
#Sta/Elev= 26
9880.768251.9321  9882.2251.84669894.274248.97959906.348247.27929930.497240.5953
9941.144238.03269954.645235.04089958.988233.9855 9966.72 231.7669976.832229.7396
9978.794229.60439994.675230.141510002.94229.664810012.52231.736110015.02232.5031
10027.09239.419510030.36241.169810039.17245.155810051.24245.317910075.39 246.309
10087.46246.507510111.61248.002610123.68250.277410137.43253.718210147.83255.5361
10154.39256.2632
#Mann= 3 , 0 , 0
9880.768    0.12       09880.768    0.12       010154.39    0.12       0
#XS Ineff= 2 , 0
       0                               0
Bank Sta=9880.768,10154.39
Exp/Cntr=0.3,0.1

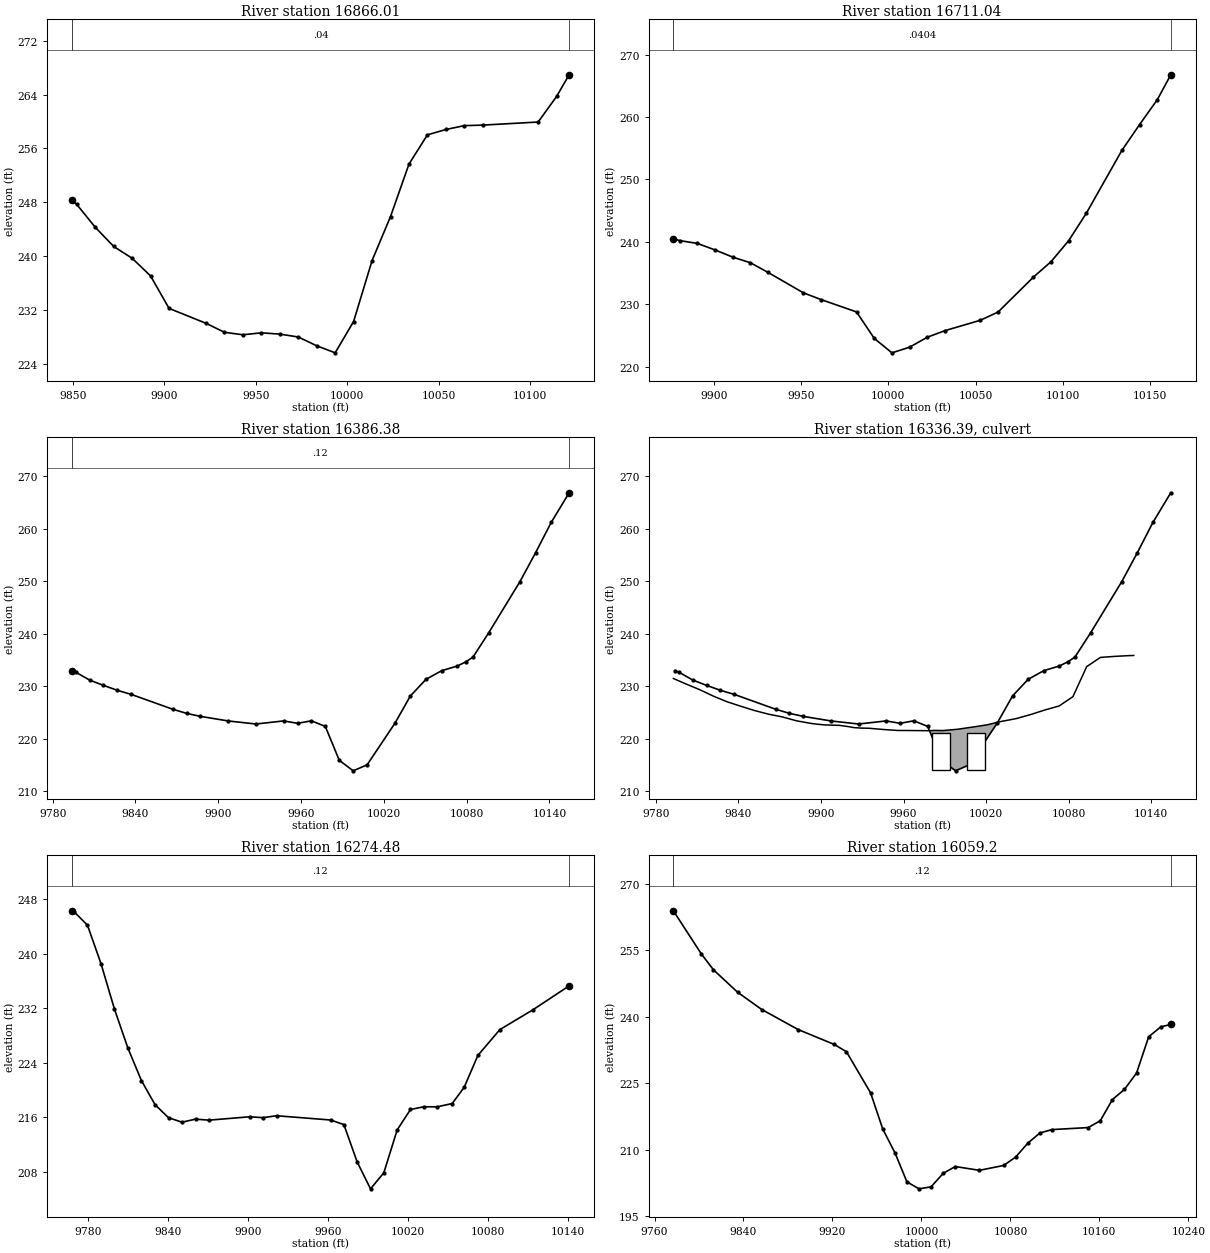
Type RM Length L Ch R = 1 ,16866.01,154.977500,154.977500,154.977500
XS GIS Cut Line= 2
920808.755134376 816167.73715606 920770.99471771 815898.20590606
#Sta/Elev= 26
9849.241248.28969852.005247.66179862.102244.2798  9872.2241.41599882.298239.6643
9892.395237.03279902.493  232.219922.688229.99639932.786228.65889942.884228.2858
9952.981228.57629963.079228.38359973.177227.95729983.274226.65129993.372225.5999
10003.47230.259610013.57239.318110023.66245.860310033.76253.654910043.86258.0116
10053.96258.809710064.06259.383710074.15259.461210104.45259.920810114.54263.7268
 10121.4266.9453
#Mann= 3 , 0 , 0
9849.241    0.04       09849.241    0.04       0 10121.4    0.04       0
#XS Ineff= 2 , 0
       0                               0
Bank Sta=9849.241,10121.4
Exp/Cntr=0.3,0.1

Type RM Length L Ch R = 1 ,16711.04,324.652400,324.652400,324.652400
XS GIS Cut Line= 2
920909.015551043816188.570489393920955.890551043815907.320489393
#Sta/Elev= 25
9876.763240.50639880.383240.20889890.521239.75079900.659238.70919910.797237.5601
9920.935236.65789931.073235.10229951.349231.83159961.487 230.7569981.762228.7789
  9991.9224.545610002.04222.229210012.18223.135510022.31224.729110032.45225.7837
10052.73227.446910062.87228.759810083.14 234.35610093.28236.837610103.42240.2143
10113.56244.625310133.83254.640410143.97 258.77510154.11262.751610161.89266.7645
#Mann= 3 , 0 , 0
9876.763  0.0404       09876.763  0.0404       010161.89  0.0404       0
#XS Ineff= 2 , 0
       0                               0
Bank Sta=9876.763,10161.89
Exp/Cntr=0.3,0.1

Type RM Length L Ch R = 1 ,16386.38,111.899400,111.899400,111.899400
XS GIS Cut Line= 4
920962.133873693816160.976338752921133.658312795816177.252380419
921196.258473052816168.488357983921306.434755103816109.644207342
#Sta/Elev= 30
9793.818232.96379796.697232.66639806.742231.16779816.787230.15149826.832229.2132
9836.877228.43679867.012225.60419877.056224.81789887.101224.24479907.191223.3721
9927.281 222.7889947.371223.37639957.416222.92099967.468223.39759977.565222.3274
9987.663215.8799 9997.76213.864810007.86215.014810028.05222.955810039.23 228.141
10050.57231.314610061.91232.953110073.24233.840310079.18234.610610084.58235.5408
10095.92240.154310118.59249.916110129.93255.433410141.27261.213210154.23266.8511
#Mann= 3 , 0 , 0
9793.818    0.12       09793.818    0.12       010154.23    0.12       0
#XS Ineff= 2 , 0
       0                               0
Bank Sta=9793.818,10154.23
Exp/Cntr=0.3,0.1

Type RM Length L Ch R = 2 ,16336.39,,,
Bridge Culvert--1,0,-1,-1, 0
Deck Dist Width WeirC Skew NumUp NumDn MinLoCord MaxHiCord MaxSubmerge Is_Ogee
21.45,69,2.6,0,45,45, , , 0.95, 0, 0,0,,
 9792.67 9801.62 9811.64 9821.44 9821.66 9831.68 9841.70 9851.73 9861.75 9871.77
 9873.31 9882.14 9892.57 9896.54 9903.00 9913.43 9920.74 9923.96 9929.14 9934.73
 9945.50 9956.06 9956.27 9967.04 9977.81 9982.99 9988.58 9999.3510009.9210010.12
10020.8910027.7510031.5510039.1810042.0210052.4910062.9510066.0910073.0910083.10
10093.1010103.1010113.1010123.1010127.33
  231.46  230.44  229.35  228.14  228.11  227.03  226.17  225.35  224.67  224.14
  224.04  223.40  222.91  222.77  222.61  222.53  222.26  222.10  222.01  221.98
  221.74  221.55  221.56  221.54  221.51  221.57  221.54  221.79  222.20  222.20
  222.64  223.07  223.31  223.68  223.83  224.60  225.48  225.71  226.23  228.00
  233.72  235.48  235.67  235.81  235.85
                                                                                
                                                                                
                                                                                
                                                                                
                                        
 9792.67 9801.62 9811.64 9821.44 9821.66 9831.68 9841.70 9851.73 9861.75 9871.77
 9873.31 9882.14 9892.57 9896.54 9903.00 9913.43 9920.74 9923.96 9929.14 9934.73
 9945.50 9956.06 9956.27 9967.04 9977.81 9982.99 9988.58 9999.3510009.9210010.12
10020.8910027.7510031.5510039.1810042.0210052.4910062.9510066.0910073.0910083.10
10093.1010103.1010113.1010123.1010127.33
  231.46  230.44  229.35  228.14  228.11  227.03  226.17  225.35  224.67  224.14
  224.04  223.40  222.91  222.77  222.61  222.53  222.26  222.10  222.01  221.98
  221.74  221.55  221.56  221.54  221.51  221.57  221.54  221.79  222.20  222.20
  222.64  223.07  223.31  223.68  223.83  224.60  225.48  225.71  226.23  228.00
  233.72  235.48  235.67  235.81  235.85
                                                                                
                                                                                
                                                                                
                                                                                
                                        
BR Coef=-1 , 0 , 0 ,, 0 ,,,0.8,-1,,0,
WSPro=,,,, 1 ,,,, 0 ,,,, 0 ,,,,-1 ,-1 ,-1 , 0 , 0 , 0 , 0 , 0
Multiple Barrel Culv=2,7,12.8,69,0.013,0.7,1,8,3,214,208,2,Culvert #1, 0, 21.45
 9987.20 9987.2010012.8010012.80
Culvert Bottom n=0.013
BC Design=,, 0 ,, 0 ,,,,,,

Type RM Length L Ch R = 1 ,16274.48,215.285300,215.285300,215.285300
XS GIS Cut Line= 4
920943.353825616816251.120569521 921129.90230318 816282.42064965
921226.306549975816283.672652855921311.442767923816262.388598367
#Sta/Elev= 30
9767.673246.31369769.343246.18799779.482244.20029789.622238.55899799.762 231.863
9809.902226.10579820.041221.34869830.181 217.8389840.321215.91459850.461215.2593
9860.601215.7061 9870.74215.5562 9901.16216.0521  9911.3215.92289921.439216.2054
9961.928215.58029971.928214.90789981.929209.4075 9991.93 205.46810001.93207.8314
10011.93214.116210021.93217.122810031.93 217.52510041.93 217.51410053.24218.0001
 10062.2220.371310072.51225.0671   10089228.859310113.74231.7575   10141 235.284
#Mann= 3 , 0 , 0
9767.673    0.12       09767.673    0.12       0   10141    0.12       0
#XS Ineff= 2 , 0
       0                               0
Bank Sta=9767.673,10141
Exp/Cntr=0.3,0.1

Type RM Length L Ch R = 1 , 16059.2,267.054600,267.054600,267.054600
XS GIS Cut Line= 2
921156.845412154816668.171183838921332.192634376816256.712850504
#Sta/Elev= 30
9776.943 263.891 9802.13254.1479    9813250.58159834.741245.51519856.481241.6252
9889.092237.12019921.702233.74629932.573232.10599954.313222.82929965.183214.7013
9976.294209.27629986.924202.78099997.794201.201610008.66201.650210019.53204.6876
 10030.4206.229810052.14205.375310073.89206.472510084.76208.372710095.63211.4937
 10106.5213.796710117.37214.558510149.98215.014110160.85216.565310171.72221.3256
10182.59223.632110193.46 227.32310204.33235.4845 10215.2 237.71910224.21238.2609
#Mann= 3 , 0 , 0
9776.943    0.12       09776.943    0.12       010224.21    0.12       0
#XS Ineff= 2 , 0
       0                               0
Bank Sta=9776.943,10224.21
Exp/Cntr=0.3,0.1

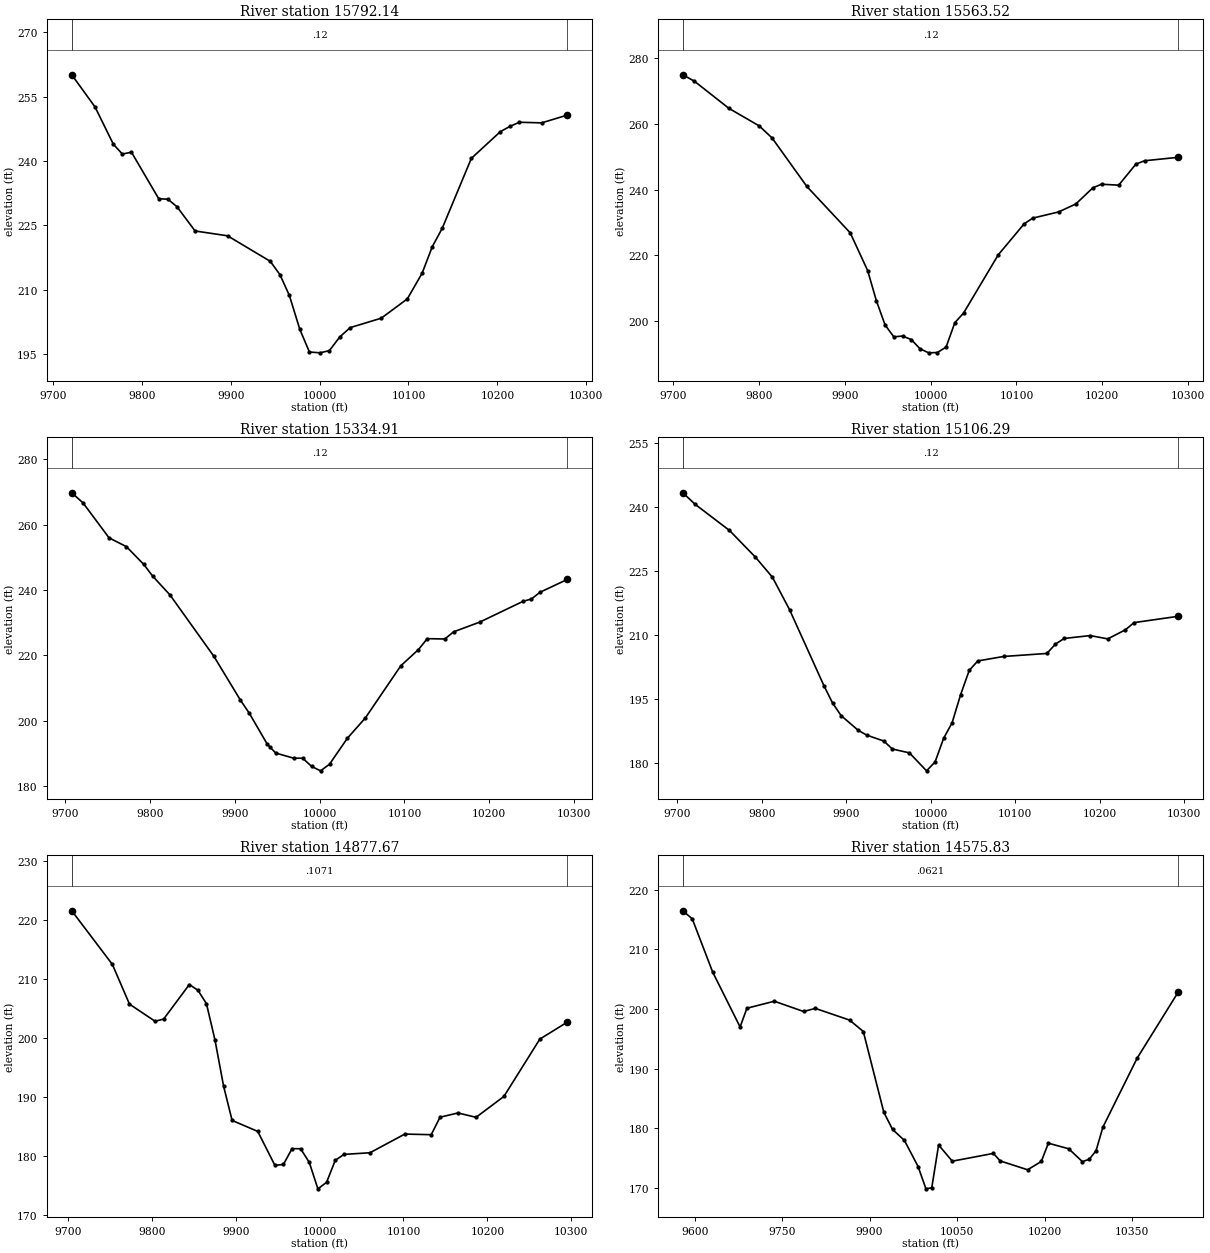
Type RM Length L Ch R = 1 ,15792.14,228.619200,228.619200,228.619200
XS GIS Cut Line= 6
921385.138399143816780.622857103 921411.86069308816656.529401021
921436.083010391816577.726526552921468.260835879816507.954910243
921534.485854852 816392.37847016921584.820888123  816264.1999871
#Sta/Elev= 30
9721.343260.09399747.553252.57379768.188243.86419778.241241.6045 9788.47242.0319
9819.158231.17289829.387231.06769839.616229.32569860.011223.65589896.532222.5293
9944.578216.57629955.437213.46439966.017208.62489977.788200.71539988.567195.4227
10000.51195.226510011.07 195.74810022.73198.9373 10034.4201.109510069.38203.3104
10098.68207.807810115.38213.826310126.66219.953810137.93 224.27810170.68 240.595
10203.32246.831110214.01248.044110224.64249.019610249.74248.874710278.65250.6977
#Mann= 3 , 0 , 0
9721.343    0.12       09721.343    0.12       010278.65    0.12       0
#XS Ineff= 2 , 0
       0                               0
Bank Sta=9721.343,10278.65
Exp/Cntr=0.3,0.1

Type RM Length L Ch R = 1 ,15563.52,228.619100,228.619100,228.619100
XS GIS Cut Line= 6
921728.519542136816818.419273589  921710.3514076816660.377315992
921679.245276881816483.471869583921672.048727566 816427.87022932
921669.279191395816346.852858155 921675.71337598 816245.60478256
#Sta/Elev= 30
9711.318275.02179724.807 273.0569765.017264.79259800.394259.43159815.327255.7606
9855.669241.03849906.326226.86999926.628215.36749936.778206.19599946.929198.8039
9957.079195.1992 9967.23195.4304 9977.38194.37229987.531191.57869997.682190.3189
10007.84190.4131   10018192.069610028.16199.494810038.32202.416410078.75 220.178
10108.98229.6285   10119231.358110149.05233.236810169.05235.652310189.05240.6062
10199.06241.676310219.07241.401910239.12247.807510249.15 248.82810288.67249.8862
#Mann= 3 , 0 , 0
9711.318    0.12       09711.318    0.12       010288.67    0.12       0
#XS Ineff= 2 , 0
       0                               0
Bank Sta=9711.318,10288.67
Exp/Cntr=0.3,0.1

Type RM Length L Ch R = 1 ,15334.91,228.619200,228.619200,228.619200
XS GIS Cut Line= 6
921982.292375327816747.993980781921961.579784816 816652.97516757
921941.351610088816575.311175132921864.749607333816331.612009166
921850.052494282 816268.37298828921835.659849256816183.318364873
#Sta/Elev= 30
9707.896269.73539721.195266.6368  9751.9255.9277 9772.37253.23969792.839247.7915
9803.074244.27289823.721238.44619875.389 219.6829906.632206.28559917.085202.2861
9937.991192.93379941.568191.87019948.443 190.0499969.529188.48179980.079188.4779
9990.629185.965910001.18184.611110011.72186.6369 10032.8 194.59810053.88200.7721
10095.75216.769610116.56221.734210126.97225.078210147.69224.972510157.95227.1644
10188.75230.140510239.67236.473610249.81237.241710259.96 239.29610292.09243.2143
#Mann= 3 , 0 , 0
9707.896    0.12       09707.896    0.12       010292.09    0.12       0
#XS Ineff= 2 , 0
       0                               0
Bank Sta=9707.896,10292.09
Exp/Cntr=0.3,0.1

Type RM Length L Ch R = 1 ,15106.29,228.619200,228.619200,228.619200
XS GIS Cut Line= 6
922176.812496786 816699.33624833922144.972489403 816523.94209634
922122.365819793816372.722728587922112.094059295816314.914741218
922091.957011039816226.532773134922062.739974577816124.534788631
#Sta/Elev= 30
 9706.68243.2943 9721.25240.59169761.904  234.469792.394228.25219812.721223.5079
9833.048215.87399873.702198.07059883.865194.04069893.985191.07319914.213187.6288
9924.327186.48749944.555185.1106 9954.67183.24079974.898182.33069995.126178.1227
10005.23180.201410015.33185.728910025.44189.414410035.54196.009110045.68201.6739
10055.84203.877810086.31204.927810137.49205.633410147.75207.8218   10158209.1484
 10188.8209.8261 10209.6209.0503 10230.4211.163110240.81212.8652 10293.3214.3528
#Mann= 3 , 0 , 0
 9706.68    0.12       0 9706.68    0.12       0 10293.3    0.12       0
#XS Ineff= 2 , 0
       0                               0
Bank Sta=9706.68,10293.3
Exp/Cntr=0.3,0.1

Type RM Length L Ch R = 1 ,14877.67,301.835300,301.835300,301.835300
XS GIS Cut Line= 6
922411.418959514816662.509794579 922363.51523034816417.360787903
922330.752719474816288.085298403922298.204221628816194.293645931
922271.637035237816138.692370746922248.977398808816098.155443376
#Sta/Elev= 30
 9704.71221.61159753.118212.52079773.497205.78989804.064202.88449814.253  203.27
9844.821 209.113 9855.01 208.1489865.199 205.8789875.388199.69329885.577191.9302
9895.766186.08539926.334184.22639946.754178.4757 9956.92178.62249967.189181.3064
9977.458181.28739987.727 178.9779997.997174.493610008.33175.593210018.67179.3172
10029.01180.329710060.04180.607810101.58183.774610133.02183.668510143.56186.6341
   10165187.353110186.44186.610410219.67 190.15510262.43199.862110295.26202.7489
#Mann= 3 , 0 , 0
 9704.71  0.1071       0 9704.71  0.1071       010295.26  0.1071       0
#XS Ineff= 2 , 0
       0                               0
Bank Sta=9704.71,10295.26
Exp/Cntr=0.3,0.1

Type RM Length L Ch R = 1 ,14575.83,615.901500,615.901500,615.901500
XS GIS Cut Line= 2
922863.442634377816658.622572727922418.130134377815934.664239393
#Sta/Elev= 30
9579.676216.4524 9595.79215.1106 9630.89  206.179677.851196.97839689.592200.1172
9736.553201.29069786.656199.57339806.995200.08739865.697198.12569889.178196.2166
9924.399182.66469939.349179.7946 9959.62  177.97  9983.1173.58649996.609 169.843
10006.58170.027110018.32177.1919 10041.8174.478110112.24175.783210123.98174.5212
10170.95173.037310194.43174.430410206.56177.493710241.39176.563510264.87174.4052
10276.61174.792610288.35176.233910300.09  180.1910358.79191.744210429.63202.8815
#Mann= 3 , 0 , 0
9579.676  0.0621       09579.676  0.0621       010429.63  0.0621       0
#XS Ineff= 2 , 0
       0                10231.05       0
Bank Sta=9579.676,10429.63
Exp/Cntr=0.3,0.1

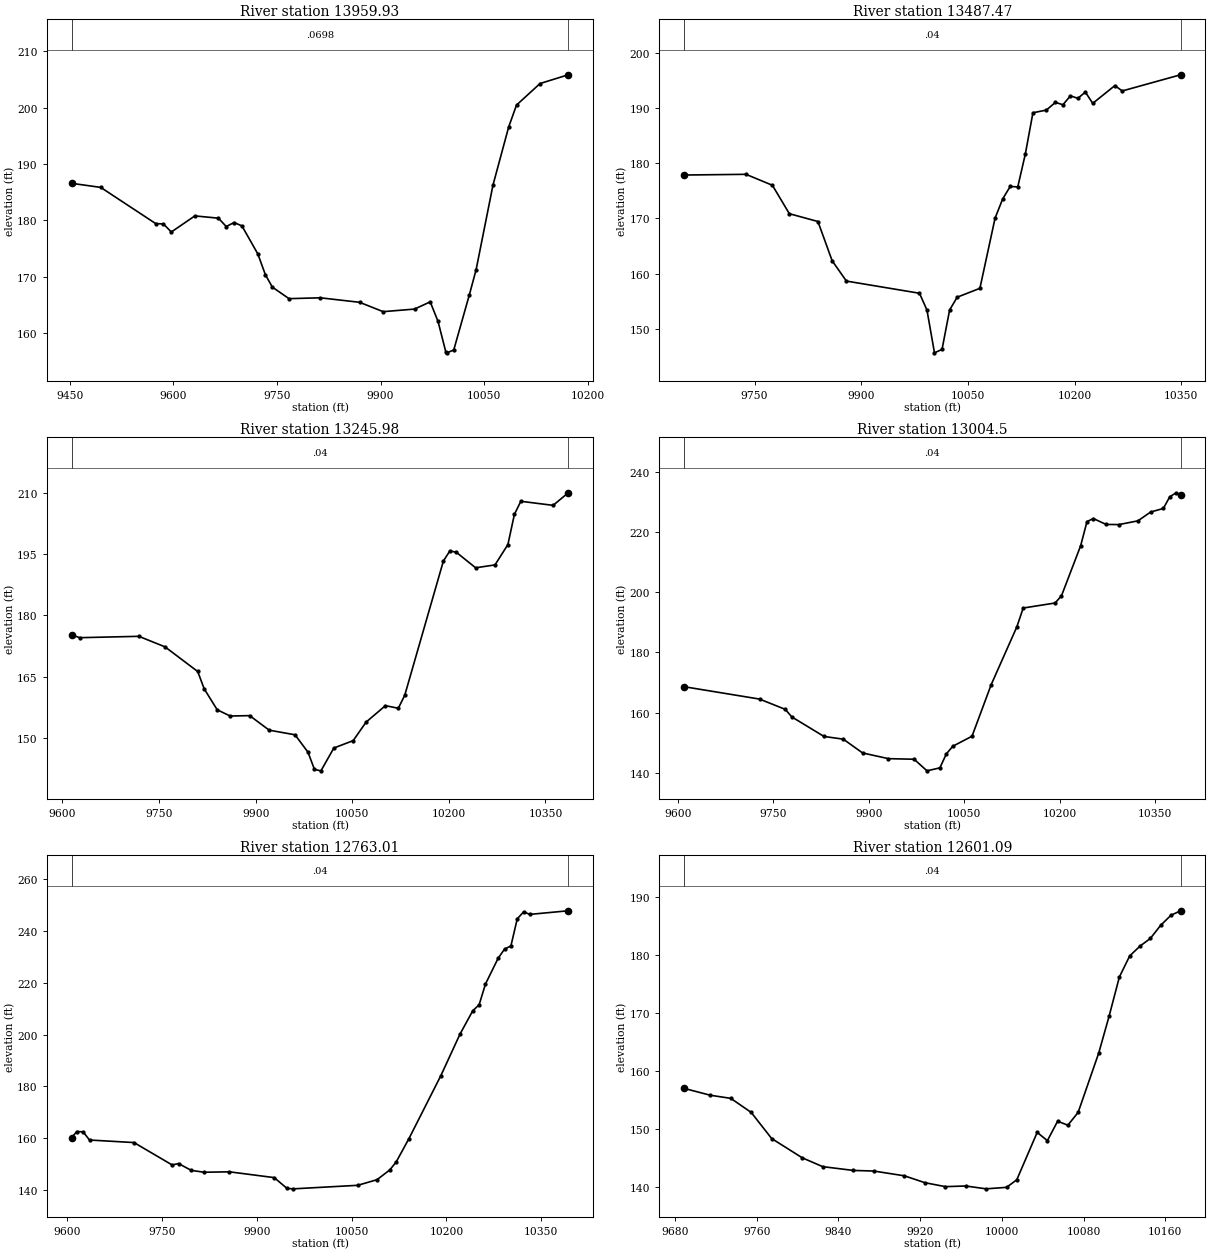
Type RM Length L Ch R = 1 ,13959.93,472.461200,472.461200,472.461200
XS GIS Cut Line= 2
922972.817634377816301.851739393922631.671801043815669.039239393
#Sta/Elev= 30
9452.975186.55969494.841185.84249574.364179.42869585.725179.34779597.086177.9296
9631.167180.78589665.249180.3809 9676.61178.9045 9687.97179.60939699.331 179.012
 9722.33174.04769733.412170.31829743.404168.15269767.494166.10889812.936166.2587
9869.739165.46199903.821163.80079949.263164.25999971.984165.54089983.345162.0619
9994.705156.58469996.284156.498510006.07157.009710028.79166.843710038.43171.2369
10062.87 186.25110085.59196.552810096.95200.443410131.03204.263910171.89 205.815
#Mann= 3 , 0 , 0
9452.975  0.0698       09452.975  0.0698       010171.89  0.0698       0
#XS Ineff= 2 , 0
       0                               0
Bank Sta=9452.975,10171.89
Exp/Cntr=0.3,0.1

Type RM Length L Ch R = 1 ,13487.47,241.485900,241.485900,241.485900
XS GIS Cut Line= 6
923128.066731575 816278.02840018923094.093968766816158.790678663
923091.800797605816050.145448444923112.707302306815960.423614013
923191.354373354815737.349564767923223.914489128815604.951720626
#Sta/Elev= 30
9650.931177.87389737.927178.00129775.037176.0184 9798.94170.86479839.105169.4525
9859.139162.33389879.174158.65949981.962156.45199992.495 153.39310003.03145.6558
10013.68146.281110024.33153.417910034.99 155.73810066.94157.343710088.24170.0485
10098.89173.519610109.54175.799710120.19175.721810130.85  181.69 10141.5189.1536
10160.35189.638310173.19191.035210183.71190.603910194.24192.221310204.76  191.77
10215.25192.908210225.63190.858710256.77194.079110267.15193.1066 10349.2196.0369
#Mann= 3 , 0 , 0
9650.931    0.04       09650.931    0.04       0 10349.2    0.04       0
#XS Ineff= 2 , 0
       0                               0
Bank Sta=9650.931,10349.2
Exp/Cntr=0.3,0.1

Type RM Length L Ch R = 1 ,13245.98,241.486000,241.486000,241.486000
XS GIS Cut Line= 6
923417.977356507816337.052938969923381.185514057816141.871950106
923367.260883181816035.899796408 923357.59775183 815932.58618467
 923354.52534765815786.392814724923367.417072436815571.509850677
#Sta/Elev= 30
9614.574175.23169626.877 174.5559718.744174.88729759.357172.30829810.053 166.291
9820.155162.04529840.327156.93599860.499155.40789890.757155.50639921.012151.9539
9961.203150.82049981.299146.56529991.347142.361410001.39142.012610021.45147.5872
10051.49149.398410071.51153.920810101.53 157.94310121.53157.305210131.53160.4783
10191.55193.300810201.56195.750310211.57195.4359 10241.6191.631410271.67192.3433
10291.71197.319210301.74204.664710311.76207.890210361.88206.895510385.43209.9687
#Mann= 3 , 0 , 0
9614.574    0.04       09614.574    0.04       010385.43    0.04       0
#XS Ineff= 2 , 0
       0                               0
Bank Sta=9614.574,10385.43
Exp/Cntr=0.3,0.1

Type RM Length L Ch R = 1 , 13004.5,241.485900,241.485900,241.485900
XS GIS Cut Line= 6
923657.321072608816291.941586555923623.733536985816088.566867578
923583.841511241815827.666738377923576.242955018815753.271160648
923571.042072338815682.170839631923564.836751278815517.944424625
#Sta/Elev= 30
9609.746168.57029728.272164.46439768.813161.04389778.949158.54869829.607 152.056
9859.971151.14849890.334 146.5739930.819144.68149971.304144.48189991.546140.6336
10011.83141.623610021.97146.251510032.07148.796410062.34152.125510092.56169.2952
10132.76188.411610142.82194.695210192.98196.364210203.01198.771210233.07215.3414
10243.08223.395910253.09224.4082 10273.1222.453310293.12222.401110323.14223.6414
10343.15226.571810363.17227.764510373.17231.618710383.18232.963910390.24232.3507
#Mann= 3 , 0 , 0
9609.746    0.04       09609.746    0.04       010390.24    0.04       0
#XS Ineff= 2 , 0
       0                               0
Bank Sta=9609.746,10390.24
Exp/Cntr=0.3,0.1

Type RM Length L Ch R = 1 ,12763.01,161.925900,161.925900,161.925900
XS GIS Cut Line= 6
923887.326625194816282.838917529923855.444906727816008.585903152
923819.851191804815807.233111508923802.979991307815695.017363951
923793.158040241 815609.81821822923784.281950112815504.575687211
#Sta/Elev= 30
9607.265160.25959615.151162.57589625.211162.45919635.271159.30519705.692158.3213
9766.052149.66619776.112150.21669796.237 147.5889816.405146.85999856.741147.0194
9927.522144.78479947.779140.60379957.907140.450810059.64141.813210090.13143.9785
10110.35147.7516 10120.5150.842810140.69159.868310191.25184.218710221.49200.2316
10241.63 209.21710251.69 211.53510261.76219.564910281.89229.562310291.94233.0363
10301.98234.250710312.01244.717710322.05 247.39410332.09246.438410392.72 247.829
#Mann= 3 , 0 , 0
9607.265    0.04       09607.265    0.04       010392.72    0.04       0
#XS Ineff= 2 , 0
       0                               0
Bank Sta=9607.265,10392.72
Exp/Cntr=0.3,0.1

Type RM Length L Ch R = 1 ,12601.09,31.775300,31.775300,31.775300
XS GIS Cut Line= 3
923991.286977082 816160.68651095923991.286977082815783.082344264
923976.096004874815675.660469279
#Sta/Elev= 30
9688.908 157.0049714.594155.82499734.594155.29039754.594152.86819774.594148.3816
9804.594145.05929824.594143.54429854.594142.89049874.594142.78879904.594141.9636
9924.594140.78569944.594140.10379964.594 140.2169984.594139.725210004.59139.9822
10014.59141.279210034.59149.432710044.59148.013210054.59151.359610064.59150.6716
10074.67152.871710094.87163.097610104.97169.407710115.07  176.1710125.17179.7941
10135.27 181.48110145.37182.794910155.47185.051910165.57 186.788   10175187.5577
#Mann= 3 , 0 , 0
9688.908    0.04       09688.908    0.04       0   10175    0.04       0
#XS Ineff= 2 , 0
       0                               0
Bank Sta=9688.908,10175
Exp/Cntr=0.3,0.1