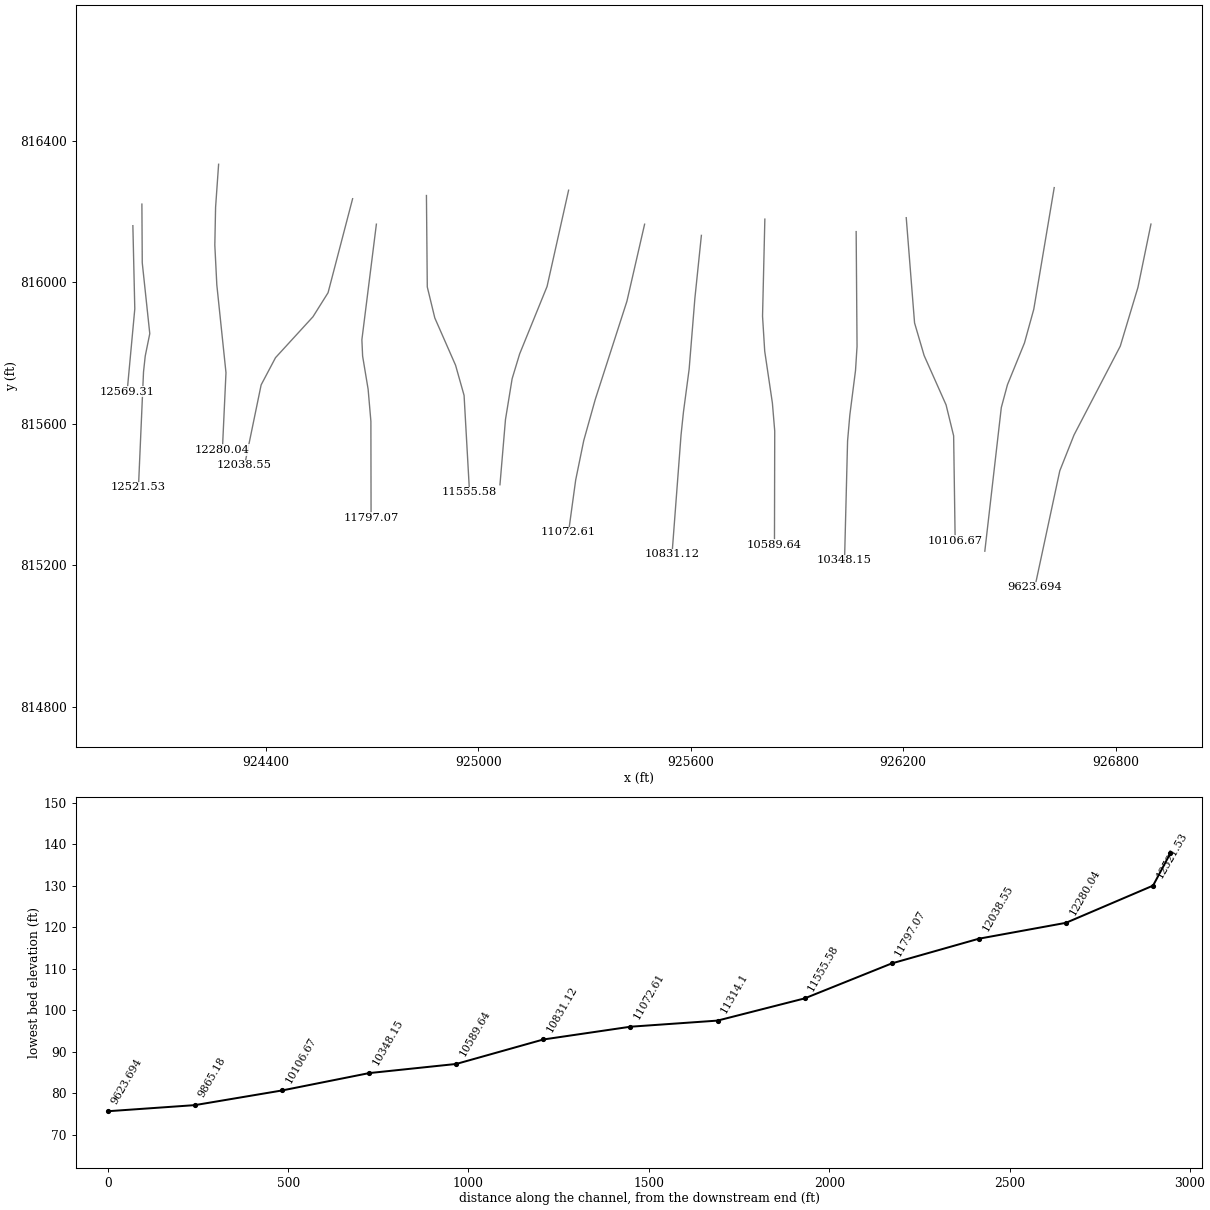
HEC-RAS study 15896_ras.prj: 15896

--- 15896_ras.g01 (geometry) --- (continued)

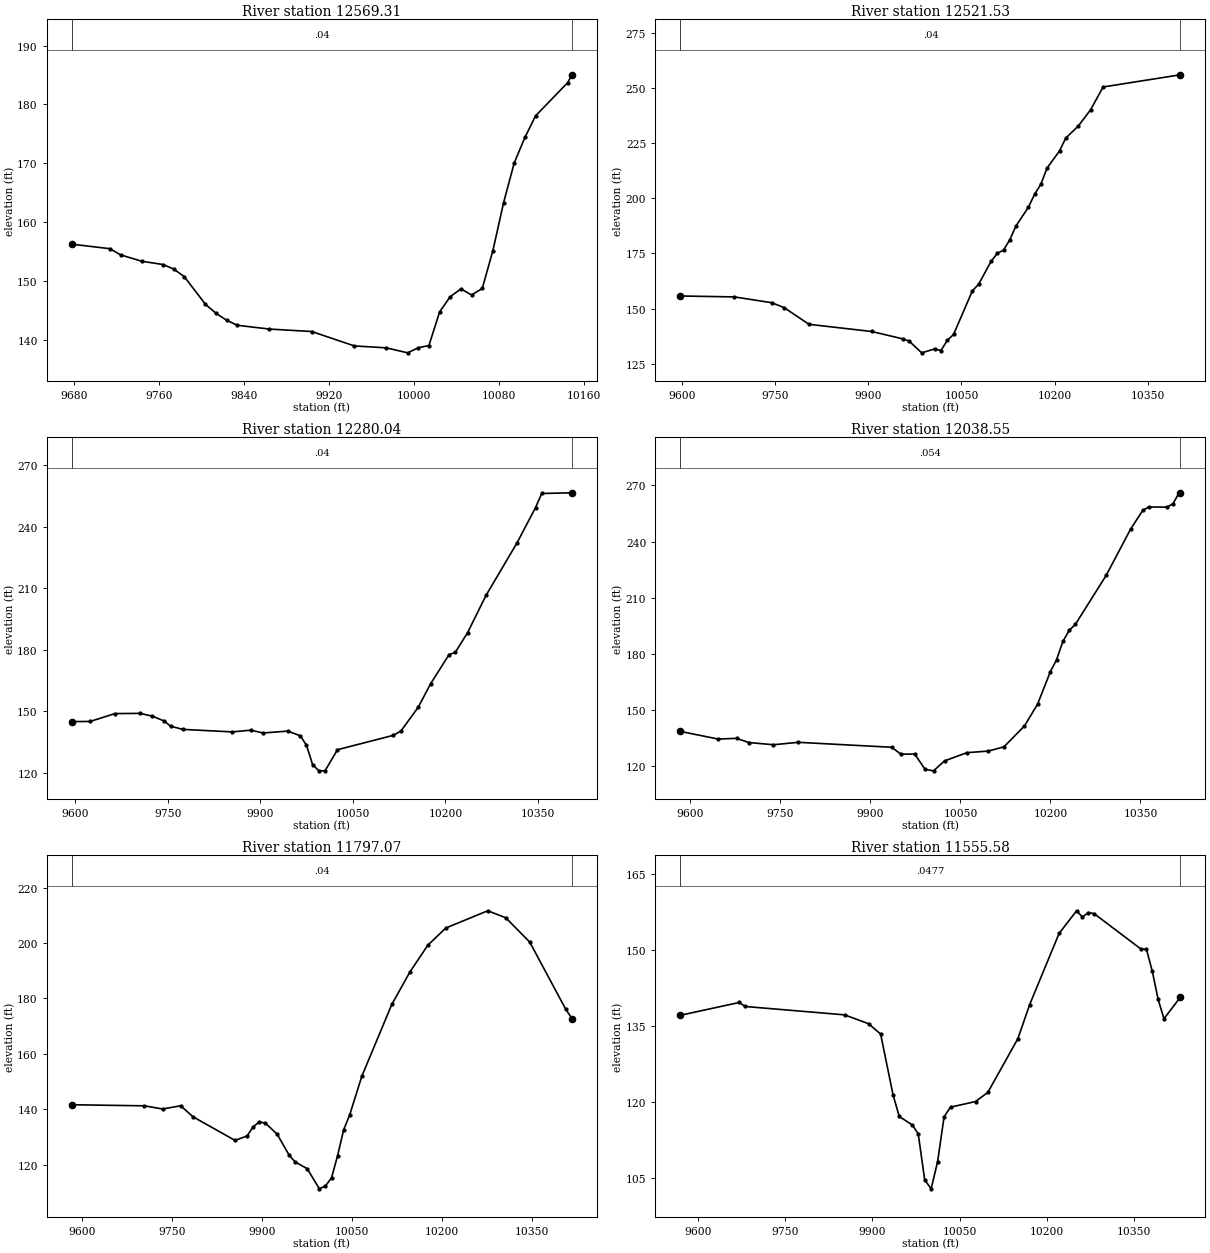
Type RM Length L Ch R = 1 ,12569.31,47.784700,47.784700,47.784700
XS GIS Cut Line= 3
924023.839060396 816160.68651095924029.264407605815925.226441503
924007.563018709815690.851441503
#Sta/Elev= 30
9678.077156.24639713.773155.48199723.775154.43819743.781153.34749763.786152.7906
9773.789152.02929783.791150.74469803.797146.02319813.799144.49129823.802 143.302
9833.805142.46099863.813141.82159903.823141.40499943.955138.95529974.083138.6276
9994.169137.777610004.21138.639110014.25 139.018 10024.3144.732510034.34147.3308
10044.38148.652110054.43147.613210064.47148.716910074.51155.169910084.55163.2967
 10094.6170.074110104.64174.393110114.68178.067210144.81 183.68710148.98185.0474
#Mann= 3 , 0 , 0
9678.077    0.04       09678.077    0.04       010148.98    0.04       0
#XS Ineff= 2 , 0
       0                               0
Bank Sta=9678.077,10148.98
Exp/Cntr=0.3,0.1

Type RM Length L Ch R = 1 ,12521.53,241.485900,241.485900,241.485900
XS GIS Cut Line= 6
924049.330234584816221.726524968924050.359240904816055.670011231
924071.594514687815855.310998044924058.762615786815791.913036195
924053.901284454815746.822543253924039.631018144815420.703086158
#Sta/Elev= 30
9597.869155.7532 9684.61155.33949744.634152.71979764.643150.49619804.764142.9249
9905.515139.67999955.842136.3231 9965.86135.32639985.985130.0163 10006.7131.7706
10016.96 131.06710027.21135.671210037.33138.3567 10067.5158.100110077.55161.0656
10097.57171.432310107.58175.065710117.59176.5145 10127.6 181.16210137.61 187.443
10157.63195.940210167.64201.831110177.65206.339810187.66213.694610207.68221.4088
10217.69227.231910237.71232.670310257.73240.063810277.75250.383910402.16 255.911
#Mann= 3 , 0 , 0
9597.869    0.04       09597.869    0.04       010402.16    0.04       0
#XS Ineff= 2 , 0
       0                               0
Bank Sta=9597.869,10402.16
Exp/Cntr=0.3,0.1

Type RM Length L Ch R = 1 ,12280.04,241.486000,241.486000,241.486000
XS GIS Cut Line= 6
 924266.05079552816334.423917582924257.511348333   816212.585052
924255.352006297816105.648478099924260.994067746815993.318588678
924286.872985507815744.789295799924276.707573014815526.037083457
#Sta/Elev= 30
9594.691 145.0569624.188145.13979664.286148.96789704.384149.07269724.416 147.784
 9744.42145.32949754.422142.82549774.426141.2655 9854.45140.03999884.475140.8856
9904.523139.50679944.638 140.4339964.731138.14969974.778133.56789984.825124.0937
9994.872121.073110004.93121.047810025.06131.3548 10115.8138.378210128.18140.5335
10155.96152.0536   10176163.461210206.02177.760810216.03178.811310236.03188.4435
10266.03206.665710316.11232.186110346.19249.454110356.21 256.31810405.29256.6649
#Mann= 3 , 0 , 0
9594.691    0.04       09594.691    0.04       010405.29    0.04       0
#XS Ineff= 2 , 0
       0                               0
Bank Sta=9594.691,10405.29
Exp/Cntr=0.3,0.1

Type RM Length L Ch R = 1 ,12038.55,241.485900,241.485900,241.485900
XS GIS Cut Line= 6
924644.630974101  816237.0049384924575.238274874815971.011260701
 924532.51464463815902.911045258924426.774511861815787.254358346
924386.185823796815710.288289749924339.333309661815482.722506472
#Sta/Elev= 30
9583.403138.33259646.373134.22599676.896 134.6229697.413132.36729738.449131.1933
9780.079132.48749935.428 129.8429951.021126.09969973.837126.22759991.124117.9871
10005.19117.2193 10023.5122.547410060.86126.950510096.53127.805410122.61130.0822
10156.63141.230410178.55152.913510199.76170.209710210.26176.775710220.76186.5364
10231.25192.393610241.67195.7003 10292.9221.886310333.54246.618310353.73256.6235
10363.82258.4877 10394.1258.407510404.19260.209810414.28266.040710416.58266.0916
#Mann= 3 , 0 , 0
9583.403   0.054       09583.403   0.054       010416.58   0.054       0
#XS Ineff= 2 , 0
       0                               0
Bank Sta=9583.403,10416.58
Exp/Cntr=0.3,0.1

Type RM Length L Ch R = 1 ,11797.07,241.485900,241.485900,241.485900
XS GIS Cut Line= 6
924711.764448129816164.991295119924670.801851234815837.963684625
924672.885780207815791.699148021924688.441254118815697.847407496
924696.237165991815607.529220687924696.776836487815334.353397133
#Sta/Elev= 30
9582.526141.62259703.617141.23029733.892140.08589764.167141.2605 9784.35137.3101
9854.937128.74099875.009130.35989885.044133.6555 9895.08135.38119905.115135.0592
9925.154131.00999945.174123.42019955.184120.98399975.408118.52369995.673111.2657
10005.83112.322910015.97115.2503 10026.1123.249210036.24132.592110046.37138.0086
10066.52 151.89310116.71177.886510146.81189.513510176.82199.234210206.83205.4176
10276.85211.638310306.85209.118310346.85200.377210406.86 176.18610417.51172.7183
#Mann= 3 , 0 , 0
9582.526    0.04       09582.526    0.04       010417.51    0.04       0
#XS Ineff= 2 , 0
       0                               0
Bank Sta=9582.526,10417.51
Exp/Cntr=0.3,0.1

Type RM Length L Ch R = 1 ,11555.58,241.486000,241.486000,241.486000
XS GIS Cut Line= 6
924853.165381461816246.060818159924855.578418453815987.282466828
924876.841302323815899.616254965924935.499754661815765.775913087
924959.505880638815680.572899282924974.870412257 815406.70488123
#Sta/Elev= 30
9570.413137.10879671.624139.63779681.626138.84299852.457 137.1919893.649135.4479
9914.445 133.4019935.708121.44959946.426117.1276 9969.18 115.4269979.109113.6821
9990.171104.610210001.26102.836810012.38108.2101 10023.5117.066710034.54118.9607
10077.62120.078910098.71121.889610150.31132.494610170.62139.227410221.09 153.262
 10251.2157.740510261.23156.492910271.27157.397810281.28157.177610361.31150.2284
10371.31150.100510381.31145.788110391.31140.243610401.31136.4174 10429.6140.6906
#Mann= 3 , 0 , 0
9570.413  0.0477       09570.413  0.0477       0 10429.6  0.0477       0
#XS Ineff= 2 , 0
       0                               0
Bank Sta=9570.413,10429.6
Exp/Cntr=0.3,0.1

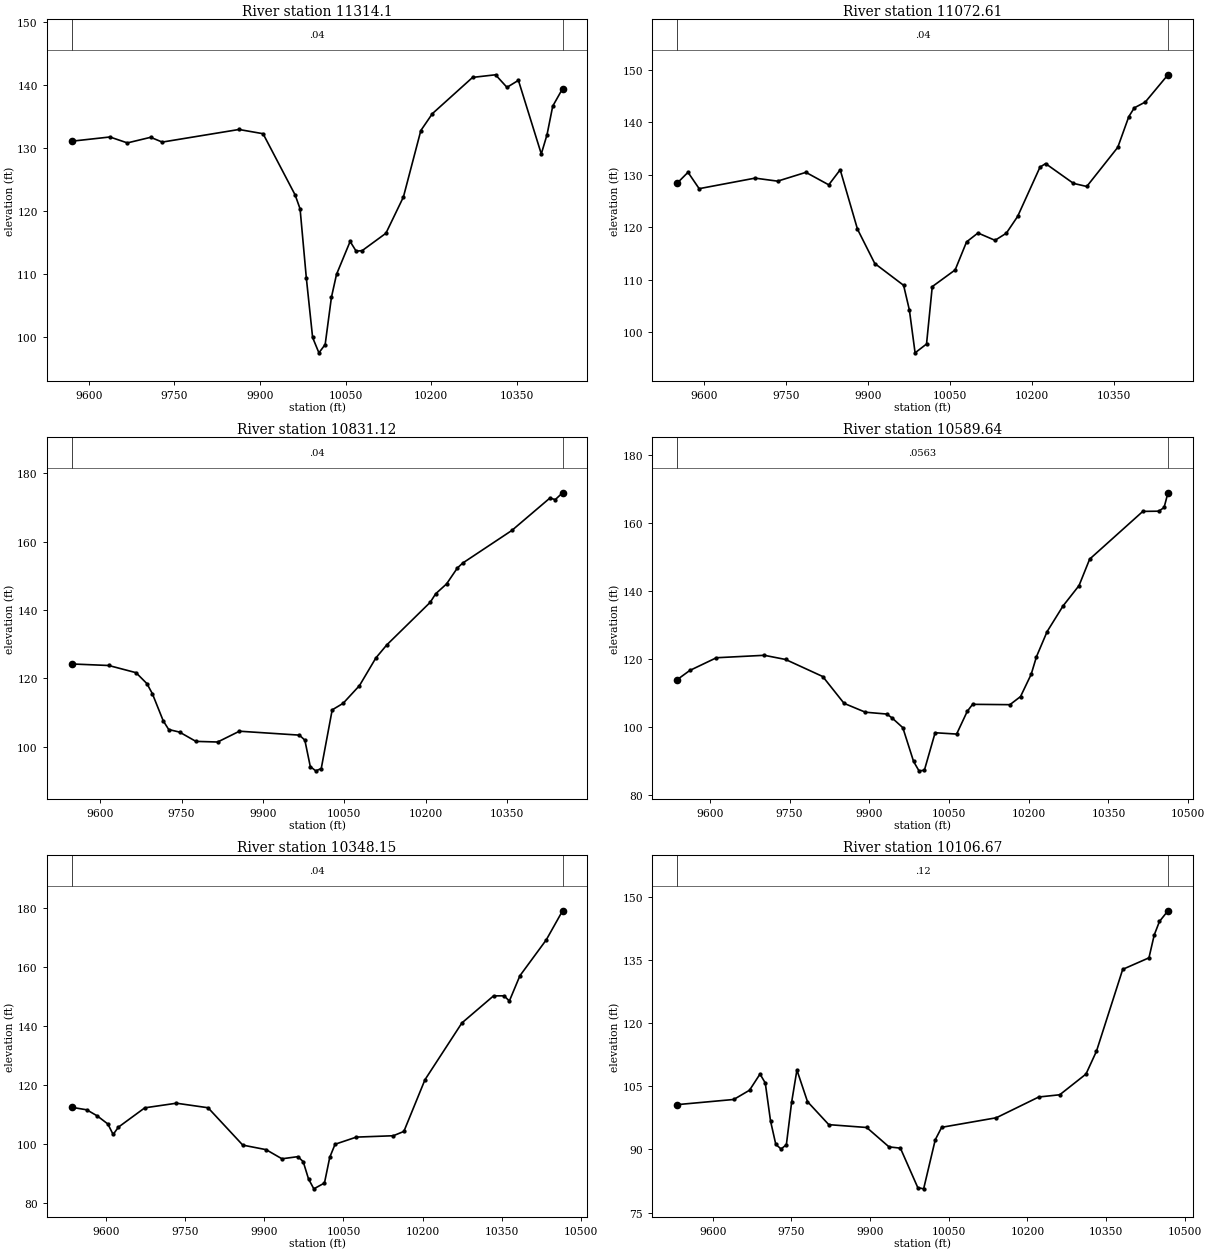
Type RM Length L Ch R = 1 , 11314.1,241.485900,241.485900,241.485900
XS GIS Cut Line= 6
925254.797743082816261.030487641925193.957931848815988.746801986
925116.469708428815797.886433818925095.263625572815727.834772265
 925076.45681427815612.275626085 925060.87259775815427.768078022
#Sta/Elev= 30
 9569.56131.05199636.866131.72389667.445130.78429708.217 131.6739728.603130.9147
9863.131132.91339905.324132.2432 9961.61122.52129970.234120.32129981.218109.3304
9992.20399.9222110003.2597.4851210014.2298.8068310025.18106.2853 10034.1109.9276
10057.96115.153910068.54113.607110079.12113.700210120.72116.452210151.39122.2076
10181.94132.748510202.16135.425910272.68141.175410312.87141.591410332.94139.5984
10352.99140.709310393.11129.036710403.14132.079910413.16136.616610430.45139.3955
#Mann= 3 , 0 , 0
 9569.56    0.04       0 9569.56    0.04       010430.45    0.04       0
#XS Ineff= 2 , 0
       0                               0
Bank Sta=9569.56,10430.45
Exp/Cntr=0.3,0.1

Type RM Length L Ch R = 1 ,11072.61,241.485900,241.485900,241.485900
XS GIS Cut Line= 6
925469.511438097 816164.89022628925419.542302501815946.952504166
925330.034903831815668.914708405  925297.4893336815552.469789904
925274.777365934815441.115254241925254.631627226815293.818363058
#Sta/Elev= 30
9550.483128.3418 9570.79130.46879591.209127.34129693.542129.35289734.851128.7759
9786.641130.45669828.469128.07349849.421 130.9499881.077119.60979912.734113.0593
9965.494108.89829976.046  104.219986.53696.0105410007.4997.6965510017.97108.6481
10059.88 111.83310080.77117.183410101.64118.882210132.89117.483610153.56118.8421
10174.23122.035310215.22131.448910225.42132.128410276.45128.352410300.83127.7586
10357.61135.230810377.79141.088810387.86142.764810408.02143.876510449.51 149.076
#Mann= 3 , 0 , 0
9550.483    0.04       09550.483    0.04       010449.51    0.04       0
#XS Ineff= 2 , 0
       0                               0
Bank Sta=9550.483,10449.51
Exp/Cntr=0.3,0.1

Type RM Length L Ch R = 1 ,10831.12,241.486000,241.486000,241.486000
XS GIS Cut Line= 6
925629.914570307816133.261539052925611.490839331815954.755518243
  925595.3105252815754.825667487925579.192107265815633.124923166
925572.440610885815568.635614712 925546.94978755815231.585677632
#Sta/Elev= 30
9547.175124.22649615.799123.77339666.065121.67339686.171118.47359696.224115.5362
9716.331107.55789726.384105.0352 9746.45104.26989776.548101.55619816.678101.3733
9856.809104.5352 9967.37103.38859977.453101.92229987.53694.168589997.61992.93326
10007.7193.59888 10027.9110.781710048.08112.702510078.26117.896410108.42125.9754
10128.49129.787610208.72142.277510218.75144.770210238.81147.653310258.87152.3408
10268.89153.790910359.15163.300210429.35 172.78210439.38172.352810452.83174.3403
#Mann= 3 , 0 , 0
9547.175    0.04       09547.175    0.04       010452.83    0.04       0
#XS Ineff= 2 , 0
       09888.548                       0
Bank Sta=9547.175,10452.83
Exp/Cntr=0.3,0.1

Type RM Length L Ch R = 1 ,10589.64,241.485900,241.485900,241.485900
XS GIS Cut Line= 6
925809.201947692816179.254591059925802.669464096815904.671014469
925808.815525308815805.539070231  925830.4968008815658.954683965
925837.103947021815579.660443122925836.340385014815257.698355712
#Sta/Elev= 30
9538.094113.77739562.368116.5409 9612.41120.27479702.481120.99349742.481119.7695
9812.481114.75249852.557106.86939892.634104.26869932.833103.72669942.912102.5798
9963.09399.720369983.35689.786379993.487 87.036910003.6287.1979910023.8698.23511
 10064.397.8430110084.37104.5466 10094.4106.584910164.56106.481910184.56108.8711
10204.57115.410510214.57120.607410234.57127.965210264.58135.514710294.58141.4813
10314.58149.2587 10414.6163.2883 10444.6163.3473 10454.6164.434710461.91168.7578
#Mann= 3 , 0 , 0
9538.094  0.0563       09538.094  0.0563       010461.91  0.0563       0
#XS Ineff= 2 , 0
       0                               0
Bank Sta=9538.094,10461.91
Exp/Cntr=0.3,0.1

Type RM Length L Ch R = 1 ,10348.15,241.485900,241.485900,241.485900
XS GIS Cut Line= 6
 926067.13887595816143.914353821926069.643149382815819.106648729
926065.315347086815751.142743583926049.211207253815624.487905555
926042.898702907815551.592820799 926034.30440182815214.035120037
#Sta/Elev= 30
 9534.28112.49819563.196111.63939583.198109.5583  9603.2106.8271  9613.2103.2708
9623.201105.75949673.205112.3097 9733.21 113.8789793.214112.3393 9859.1199.66729
9903.30698.126979933.403 95.0274 9963.6495.752549973.71894.051819983.79788.19777
9993.87684.8343210014.0486.8079610024.1295.55798 10034.299.9616210074.45102.3784
10144.66102.845510164.67104.3122 10204.7121.846910274.73141.102610334.74150.2845
10354.75150.306510364.75148.539510384.75157.107210434.76169.286710465.73179.1491
#Mann= 3 , 0 , 0
 9534.28    0.04       0 9534.28    0.04       010465.73    0.04       0
#XS Ineff= 2 , 0
       0                               0
Bank Sta=9534.28,10465.73
Exp/Cntr=0.3,0.1

Type RM Length L Ch R = 1 ,10106.67,241.485900,241.485900,241.485900
XS GIS Cut Line= 6
926208.605633713816183.327128268926232.109205763815885.690670645
926259.158667285815793.321301226  926321.1160697815653.784773063
926342.520158515815566.172455759926346.843721789815268.784054202
#Sta/Elev= 30
9531.843100.64119640.219101.87499670.265104.07049690.295107.9128 9700.31105.7906
9710.34596.772929720.40791.196199730.46990.116599740.531  91.1189750.594101.2343
9760.656108.86599780.816101.35729821.43395.893829893.73795.217449936.25290.61265
9957.97790.30962 9991.1380.9365910002.2780.6466810024.4392.3065110036.6895.26107
10140.8897.5297310221.74102.4599 10261.8102.991610311.83 107.91110331.83 113.347
10381.85132.782510431.89135.5199 10441.9140.932810451.91144.159710468.14146.6946
#Mann= 3 , 0 , 0
9531.843    0.12       09531.843    0.12       010468.14    0.12       0
#XS Ineff= 2 , 0
       0 9886.51                       0
Bank Sta=9531.843,10468.14
Exp/Cntr=0.3,0.1

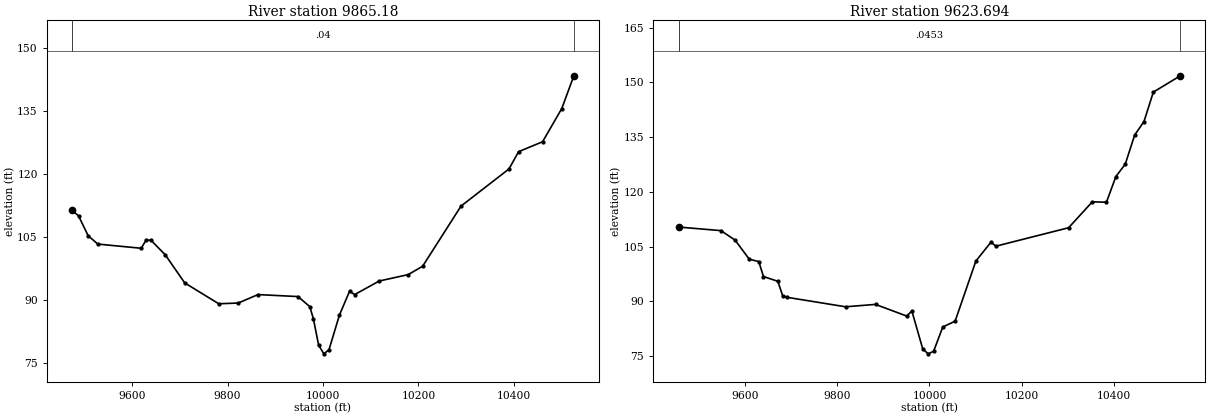
Type RM Length L Ch R = 1 , 9865.18,241.486000,241.486000,241.486000
XS GIS Cut Line= 6
926626.673156713816268.404642848926568.893603169815924.198748474
926542.625784708815828.987408345926494.475750898815710.545649038
926477.210088889815646.296554164926430.617040365815239.807035881
#Sta/Elev= 30
 9474.17111.29239487.711109.98249507.915105.23559528.119103.25699619.038102.2543
 9629.14104.16829639.242104.19879669.612100.67899710.24594.010269781.60789.03955
9822.50789.215239863.78191.225859947.65690.755329972.32888.368329979.95585.47018
9990.87379.20002 10001.877.1154510012.6578.0949810034.3486.2816810055.8392.06077
10066.3191.2212610117.9194.4571410178.6695.9859610208.8997.9796610289.36112.3012
 10389.9121.150210410.01125.255710460.28127.6288 10500.5135.529310525.83 143.335
#Mann= 3 , 0 , 0
 9474.17    0.04       0 9474.17    0.04       010525.83    0.04       0
#XS Ineff= 2 , 0
       0                               0
Bank Sta=9474.17,10525.83
Exp/Cntr=0.3,0.1

Type RM Length L Ch R = 1 ,9623.694,241.485900,241.485900,241.485900
XS GIS Cut Line= 6
926899.956860018 816165.25598884926863.160979287815986.008593823
 926813.27771028815819.910214141926682.672856817815568.758777702
926642.400355993815467.248840965926571.747115232815137.290770252
#Sta/Elev= 30
 9456.39110.36819548.262 109.3849578.897106.79059609.668101.56069630.182100.9126
9640.44996.811099671.529   95.519681.88991.601959692.24891.10939 9818.1988.53158
9883.15289.181499950.55985.999289962.00187.349459985.50676.988429997.31475.64327
10009.0976.3509910028.9883.0083210055.6384.5820910100.64101.057310133.31106.2184
 10144.2105.130310301.57110.179310352.93117.273710383.57117.165810403.93124.1832
 10424.3127.596810444.63135.552810464.89139.269210485.15147.327510543.61151.7925
#Mann= 3 , 0 , 0
 9456.39  0.0453       0 9456.39  0.0453       010543.61  0.0453       0
#XS Ineff= 2 , 0
       0                               0
Bank Sta=9456.39,10543.61
Exp/Cntr=0.3,0.1