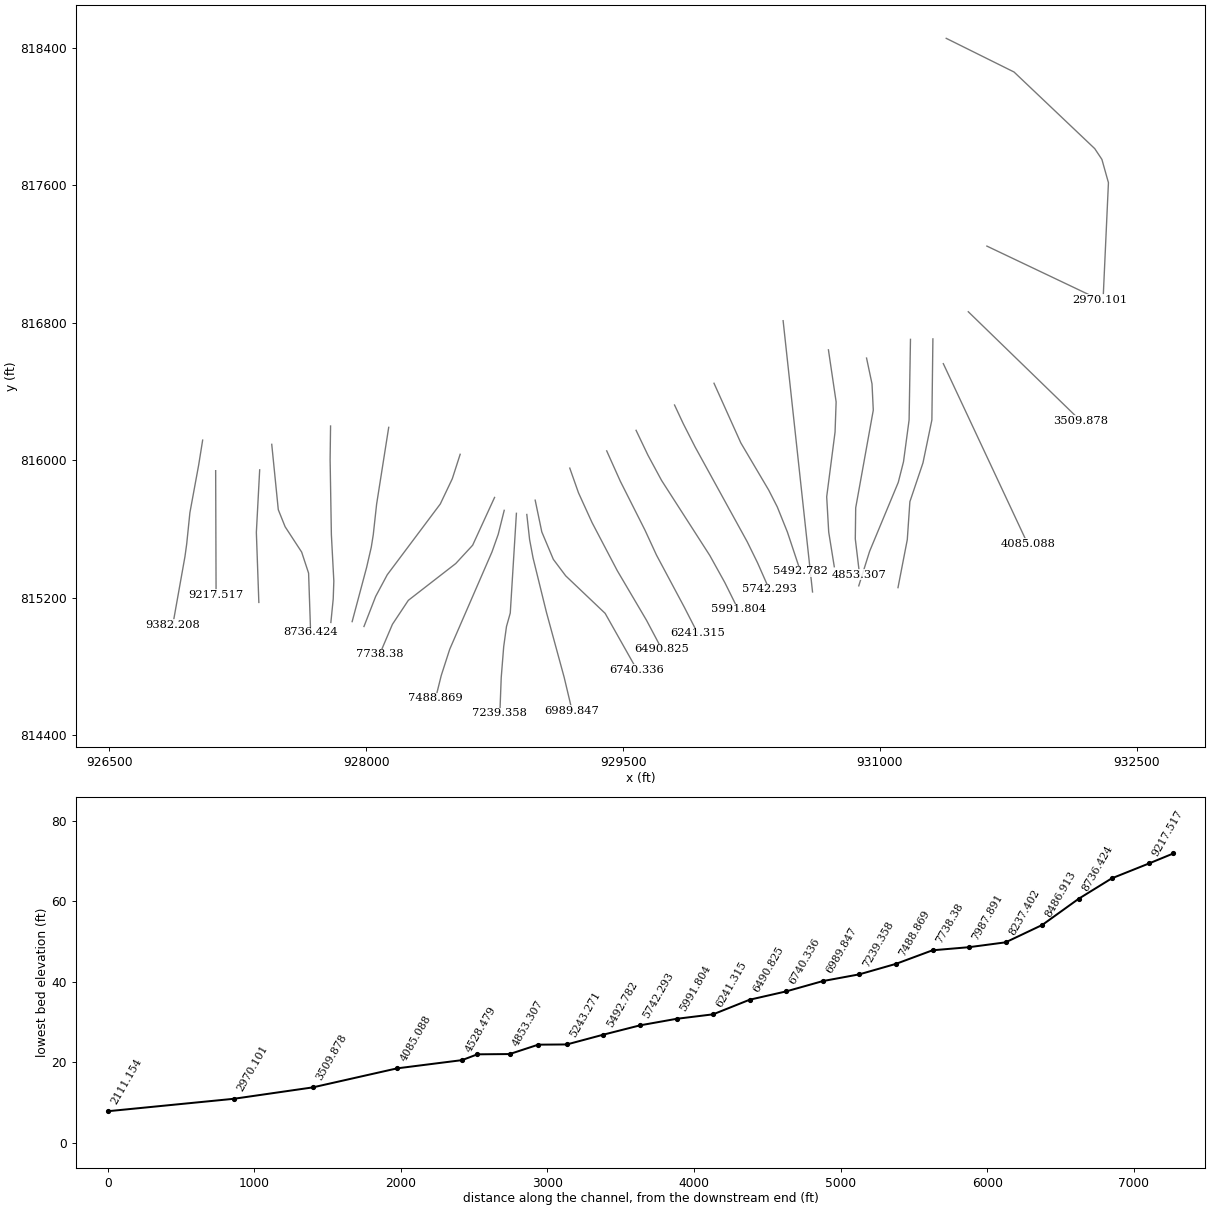
HEC-RAS study 15896_ras.prj: 15896

--- 15896_ras.g01 (geometry) --- (continued)

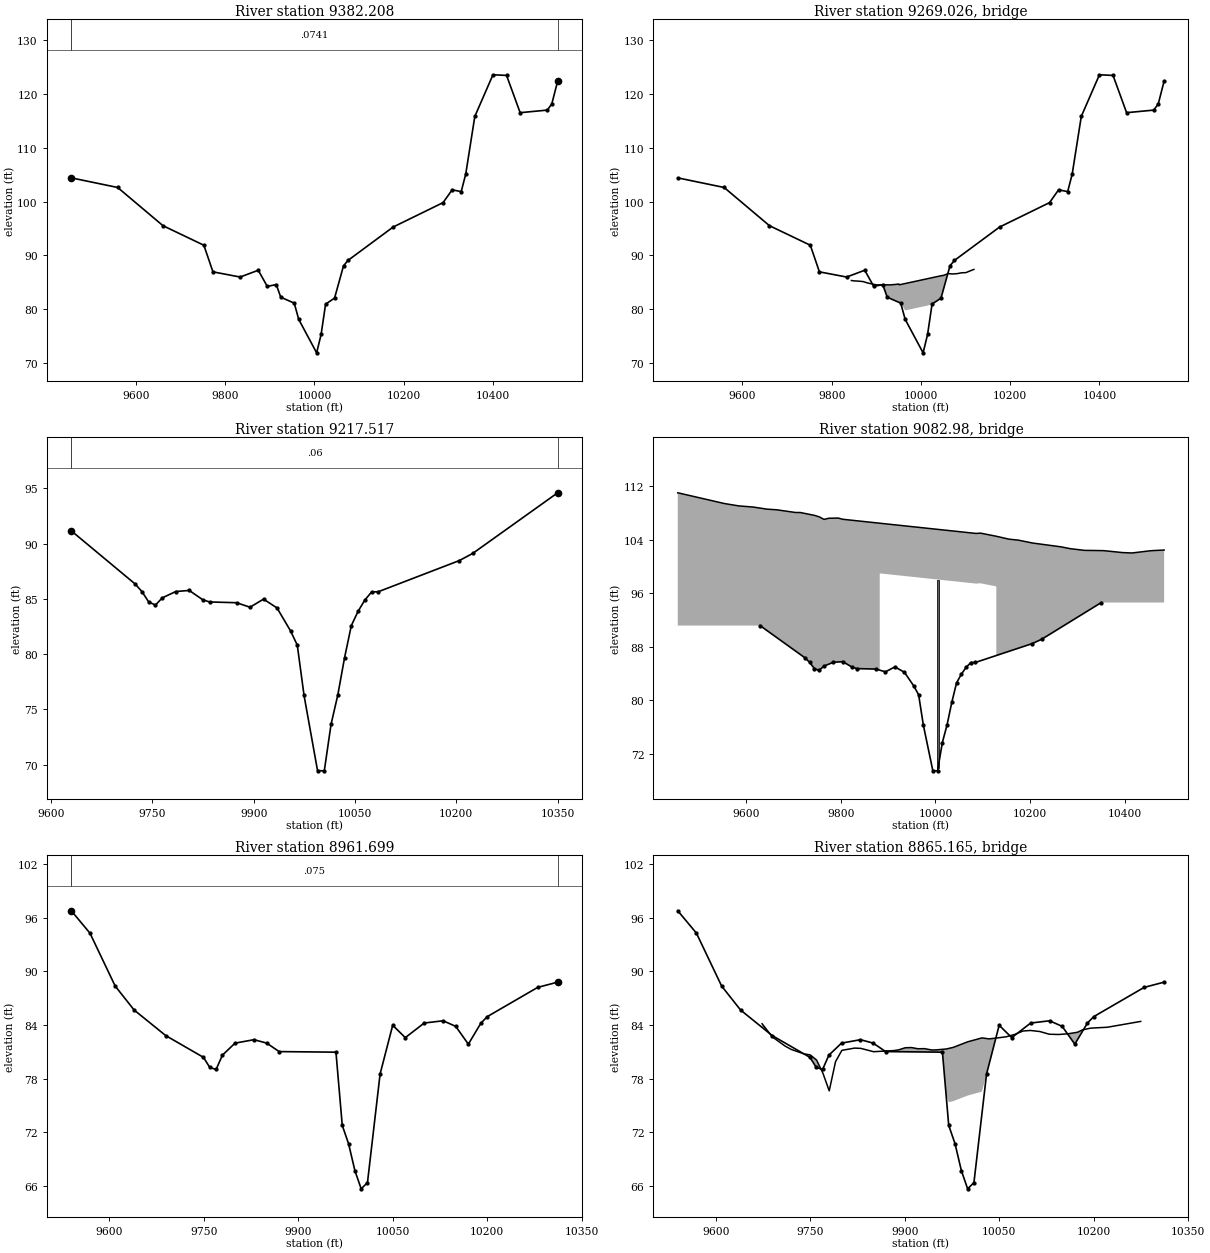
Type RM Length L Ch R = 1 ,9382.208,164.691100,164.691100,164.691100
XS GIS Cut Line= 6
927044.258709136816117.610497079927021.057832919815973.272007691
926969.786730711815695.719388279  926951.0925731815513.839630197
926940.938426444815440.436825436926869.699794515815042.034670578
#Sta/Elev= 30
9454.929104.43199558.856 102.6449660.43595.539629752.04791.905899772.40586.95987
9833.40285.995569873.96887.256569894.18384.25714 9914.3484.589339924.41882.24028
9954.61681.145279964.65478.1264910004.8171.9022910014.8675.32514 10024.980.96232
10044.9982.0729810065.0888.0806310075.1789.0913610176.37 95.2938 10288.299.82791
10308.53102.205910328.86101.875510339.03105.145210359.36115.854710400.03123.5963
10430.52123.480310460.94  116.5510521.79117.029210531.93118.183810545.07122.4404
#Mann= 3 , 0 , 0
9454.929  0.0741       09454.929  0.0741       010545.07  0.0741       0
#XS Ineff= 2 , 0
       0                               0
Bank Sta=9454.929,10545.07
Exp/Cntr=0.3,0.1

Type RM Length L Ch R = 3 ,9269.026,,,
BEGIN DESCRIPTION:
END DESCRIPTION:
Bridge Culvert--1,0,-1,-1, 0
Deck Dist Width WeirC Skew NumUp NumDn MinLoCord MaxHiCord MaxSubmerge Is_Ogee
62.990550,38.710000,2.6,0, 28, 28, , , 0.95, 0, 0,0,,
 9844.08 9850.24 9860.27 9870.29 9880.32 9890.35 9900.38 9910.40 9920.43 9930.46
 9937.37 9940.49 9949.96 9949.96 9950.51 9951.3910034.9310034.9310046.0810050.79
10060.8210070.8410072.5010080.8710090.9010100.9310110.9510118.69
   85.35   85.28   85.23   85.15   84.89   84.71   84.53   84.53   84.55   84.54
   84.58   84.60   84.69   84.69   84.69   84.55   86.05   86.05   86.25   86.30
   86.64   86.56   86.58   86.62   86.78   86.82   87.16   87.41
 -914.65 -914.72 -914.77 -914.85 -915.11 -915.29 -915.47 -915.47 -915.45 -915.46
 -915.42 -915.40 -915.31   79.69   79.69   79.55   81.05 -913.95 -913.75 -913.70
 -913.36 -913.44 -913.42 -913.38 -913.22 -913.18 -912.84 -912.59
 9844.08 9850.24 9860.27 9870.29 9880.32 9890.35 9900.38 9910.40 9920.43 9930.46
 9937.37 9940.49 9950.51 9951.39 9963.02 9963.0210046.0810047.9910047.9910050.79
10060.8210070.8410072.5010080.8710090.9010100.9310110.9510118.69
   85.35   85.28   85.23   85.15   84.89   84.71   84.53   84.53   84.55   84.54
   84.58   84.60   84.69   84.55   84.76   84.76   86.25   86.27   86.27   86.30
   86.64   86.56   86.58   86.62   86.78   86.82   87.16   87.41
 -914.65 -914.72 -914.77 -914.85 -915.11 -915.29 -915.47 -915.47 -915.45 -915.46
 -915.42 -915.40 -915.31 -915.45 -915.24   79.76   81.25   81.27 -913.73 -913.70
 -913.36 -913.44 -913.42 -913.38 -913.22 -913.18 -912.84 -912.59
BR Coef=-1 , 0 , 0 ,, 0 ,,,0.8,0,1,0,
WSPro=,,,, 1 ,,,, 0 ,,,, 0 ,,,,-1 ,-1 ,-1 , 0 , 0 , 0 , 0 , 0
BC Design=,, 0 ,, 0 ,,,,,,

Type RM Length L Ch R = 1 ,9217.517,255.817900,255.817900,255.817900
XS GIS Cut Line= 2
927120.232804281815939.693933157927122.658116714815219.376140545
#Sta/Elev= 30
9629.84591.154769724.53986.338189734.53985.652569744.53984.712789754.53984.44168
9764.53985.08781 9784.5485.66282 9804.54 85.7609 9824.5484.91766 9834.5484.71992
 9874.54 84.6502 9894.5484.24216 9914.5484.97594 9934.5484.17454 9954.5482.10239
9964.54180.811669974.54176.263069994.54169.4519410004.54 69.435410014.5473.64304
10024.5476.3018810034.5479.6704510044.5482.5748110054.5483.8694310064.5484.88677
10074.5485.6201510084.5485.6457910204.5488.4646810224.5489.1191210350.1794.59975
#Mann= 3 , 0 , 0
9629.845    0.06       09629.845    0.06       010350.17    0.06       0
#XS Ineff= 2 , 0
       0                               0
Bank Sta=9629.845,10350.17
Exp/Cntr=0.3,0.1

Type RM Length L Ch R = 3 , 9082.98,,,
BEGIN DESCRIPTION:
END DESCRIPTION:
Bridge Culvert--1,0,-1,-1, 0
Deck Dist Width WeirC Skew NumUp NumDn MinLoCord MaxHiCord MaxSubmerge Is_Ogee
66.408950,123.000000,2.6,0, 31, 31, , , 0.95, 0, 0,0,,
 9456.19 9554.73 9584.79 9614.96 9644.85 9664.85 9704.85 9714.85 9744.85 9754.85
 9764.85 9774.85 9794.85 9804.30 9882.50 9882.5010085.9610094.8510128.5010128.50
10154.8510174.8510204.8510264.8510284.8510314.8510354.8510394.8510414.8510454.85
10482.71
  111.01  109.40  109.05  108.88  108.56  108.47  108.06  108.06  107.63  107.41
  107.03  107.20  107.23  107.05  106.46  106.46  104.93  104.98  104.51  104.51
  104.08  103.93  103.50  102.93  102.65  102.40  102.36  102.07  102.01  102.35
  102.45
 -888.99 -890.60 -890.95 -891.12 -891.44 -891.53 -891.94 -891.94 -892.37 -892.59
 -892.97 -892.80 -892.77 -892.95 -893.54   98.96   97.43   97.48   97.01 -895.49
 -895.92 -896.07 -896.50 -897.07 -897.35 -897.60 -897.64 -897.93 -897.99 -897.65
 -897.55
 9456.19 9554.73 9584.79 9614.96 9644.85 9664.85 9704.85 9714.85 9744.85 9754.85
 9764.85 9774.85 9794.85 9804.30 9874.69 9874.6910085.9610094.8510120.6910120.69
10154.8510174.8510204.8510264.8510284.8510314.8510354.8510394.8510414.8510454.85
10482.71
  111.01  109.40  109.05  108.88  108.56  108.47  108.06  108.06  107.63  107.41
  107.03  107.20  107.23  107.05  106.52  106.52  104.93  104.98  104.64  104.64
  104.08  103.93  103.50  102.93  102.65  102.40  102.36  102.07  102.01  102.35
  102.45
 -888.99 -890.60 -890.95 -891.12 -891.44 -891.53 -891.94 -891.94 -892.37 -892.59
 -892.97 -892.80 -892.77 -892.95 -893.48   99.02   97.43   97.48   97.14 -895.36
 -895.92 -896.07 -896.50 -897.07 -897.35 -897.60 -897.64 -897.93 -897.99 -897.65
 -897.55
Pier Skew, UpSta & Num, DnSta & Num=  ,10005.50, 2 ,9997.69, 2 , 0 , 0 , 0 ,,
    4.00    4.00
 -894.46  105.54
    4.00    4.00
 -894.41  105.59
BR Coef=-1 , 0 , 0 ,, 0 ,,,0.8,0,1,0,
WSPro=,,,, 1 ,,,, 0 ,,,, 0 ,,,,-1 ,-1 ,-1 , 0 , 0 , 0 , 0 , 0
BC Design=,, 0 ,, 0 ,,,,,,

Type RM Length L Ch R = 1 ,8961.699,225.275300,225.275300,225.275300
XS GIS Cut Line= 3
927377.315922183815944.544558023927357.913422719815580.747693068
927372.465297317815173.295204317
#Sta/Elev= 30
9539.73396.75113 9569.3294.257059609.37688.349029639.41985.67471 9689.4982.82517
9749.575 80.3857 9759.5979.258919769.60479.036019779.61880.637299799.64681.97438
9829.68982.359879849.718 81.98289869.746 81.0307 9959.8380.966819969.83772.78863
9979.84370.749019989.84967.754279999.85665.7098210009.8666.4075110029.8778.52175
10049.8983.97048 10069.982.5892810099.9284.2186210129.9484.4718110149.9583.84726
10169.9681.8612410189.9884.2120110199.9884.9328110280.03 88.198810311.7688.78574
#Mann= 3 , 0 , 0
9539.733   0.075       09539.733   0.075       010311.76   0.075       0
#XS Ineff= 2 , 0
       0                               0
Bank Sta=9539.733,10311.76
Exp/Cntr=0.3,0.1

Type RM Length L Ch R = 3 ,8865.165,,,
BEGIN DESCRIPTION:
END DESCRIPTION:
Bridge Culvert--1,0,-1,-1, 0
Deck Dist Width WeirC Skew NumUp NumDn MinLoCord MaxHiCord MaxSubmerge Is_Ogee
70.152650,84.970000,2.6,0, 43, 42, , , 0.95, 0, 0,0,,
 9673.60 9689.73 9709.82 9719.87 9739.96 9750.00 9760.05 9770.09 9780.14 9790.18
 9800.23 9820.32 9830.36 9850.46 9882.20 9890.69 9900.74 9910.80 9920.85 9931.55
 9942.92 9949.30 9949.30 9965.65 9977.02 9999.7610022.5010033.8410046.0810046.08
10060.8310074.3110087.7910099.5810114.4910129.4010144.3110159.2310174.2910181.90
10195.1610221.6810274.56
   84.14   82.68   81.66   81.27   80.78   80.66   80.09   78.63   76.65   79.91
   81.17   81.42   81.39   81.02   81.14   81.23   81.46   81.48   81.35   81.36
   81.21   81.22   81.22   81.32   81.50   82.12   82.56   82.45   82.55   82.55
   82.68   82.94   83.33   83.39   83.27   82.97   82.94   83.02   83.19   83.45
   83.65   83.75   84.40
 -915.86 -917.32 -918.34 -918.73 -919.22 -919.34 -919.91 -921.37 -923.35 -920.09
 -918.83 -918.58 -918.61 -918.98 -918.86 -918.77 -918.54 -918.52 -918.65 -918.64
 -918.79 -918.78   75.22   75.32   75.50   76.12   76.56   76.45   76.55 -917.45
 -917.32 -917.06 -916.67 -916.61 -916.73 -917.03 -917.06 -916.98 -916.81 -916.55
 -916.35 -916.25 -915.60
 9673.60 9689.73 9709.82 9719.87 9739.96 9750.00 9760.05 9770.09 9780.14 9790.18
 9800.23 9820.32 9830.36 9850.46 9882.20 9890.69 9900.74 9910.80 9920.85 9931.55
 9942.92 9957.24 9957.24 9977.02 9999.7610022.5010033.8410054.0210054.0210060.83
10074.3110087.7910099.5810114.4910129.4010144.3110159.2310174.2910181.9010195.16
10221.6810274.56
   84.14   82.68   81.66   81.27   80.78   80.66   80.09   78.63   76.65   79.91
   81.17   81.42   81.39   81.02   81.14   81.23   81.46   81.48   81.35   81.36
   81.21   81.26   81.26   81.50   82.12   82.56   82.45   82.63   82.63   82.68
   82.94   83.33   83.39   83.27   82.97   82.94   83.02   83.19   83.45   83.65
   83.75   84.40
 -915.86 -917.32 -918.34 -918.73 -919.22 -919.34 -919.91 -921.37 -923.35 -920.09
 -918.83 -918.58 -918.61 -918.98 -918.86 -918.77 -918.54 -918.52 -918.65 -918.64
 -918.79 -918.74   75.26   75.50   76.12   76.56   76.45   76.63 -917.37 -917.32
 -917.06 -916.67 -916.61 -916.73 -917.03 -917.06 -916.98 -916.81 -916.55 -916.35
 -916.25 -915.60
BR Coef=-1 , 0 , 0 ,, 0 ,,,0.8,0,1,0,
WSPro=,,,, 1 ,,,, 0 ,,,, 0 ,,,,-1 ,-1 ,-1 , 0 , 0 , 0 , 0 , 0
BC Design=,, 0 ,, 0 ,,,,,,

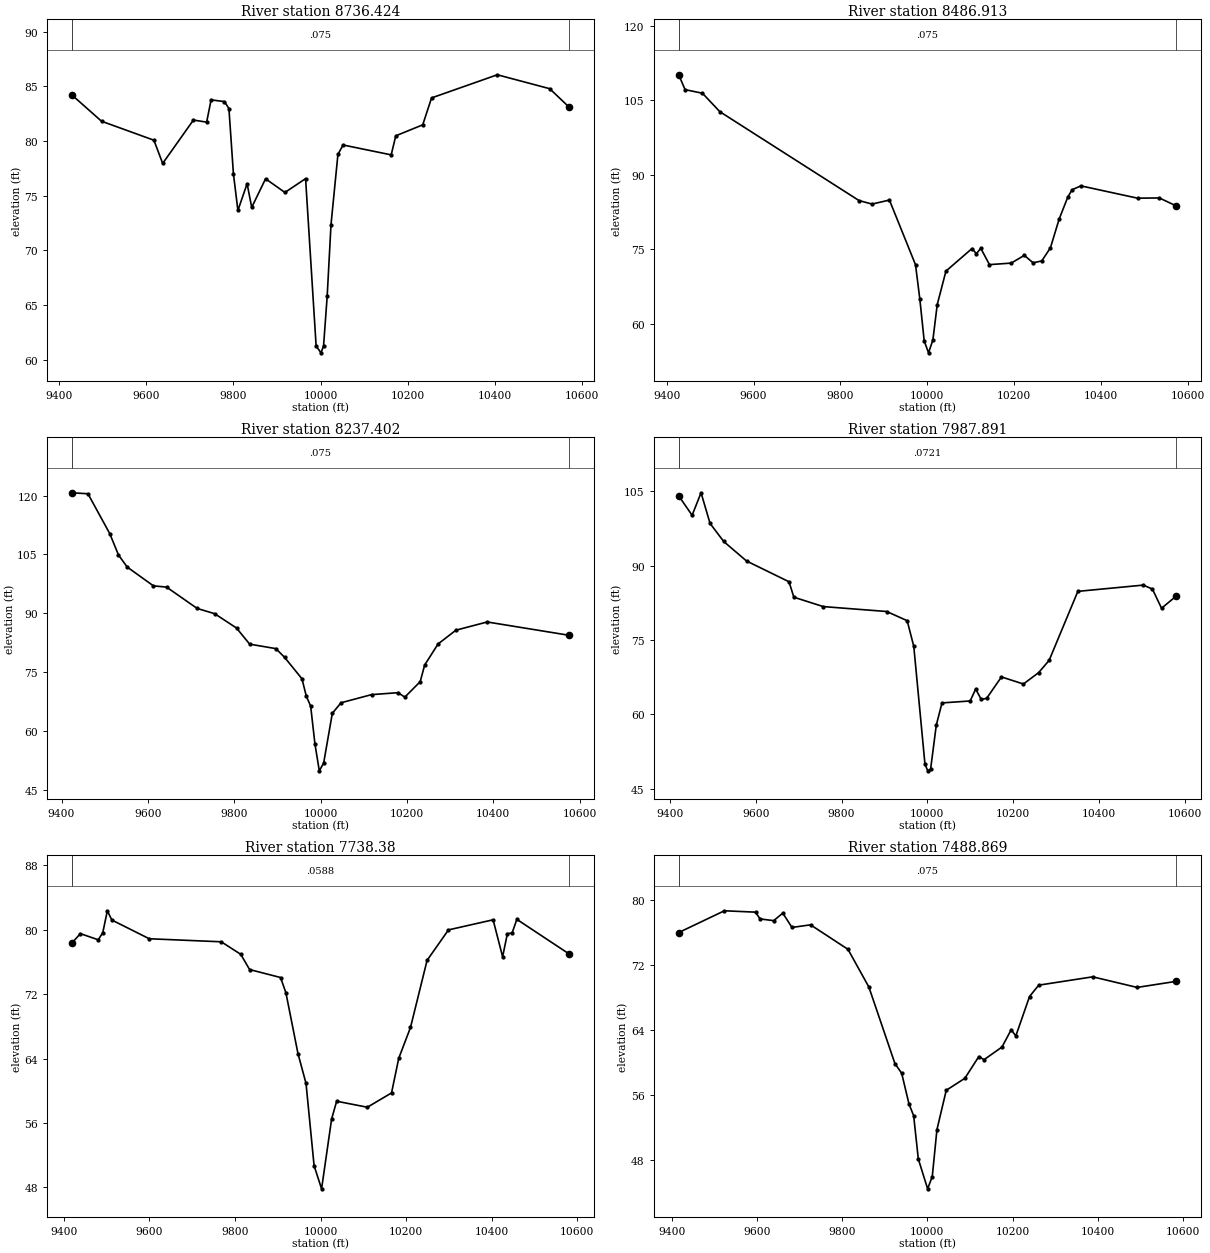
Type RM Length L Ch R = 1 ,8736.424,249.510900,249.510900,249.510900
XS GIS Cut Line= 6
927447.795606731816093.069643837927486.037407161815712.715946155
927526.001722631815613.487655479927622.501415511815466.211226511
927663.032342156815343.500570126927674.820414411815000.337255521
#Sta/Elev= 30
9429.62584.212659497.71281.809939617.90380.075429637.945 77.95359708.47881.91706
9738.82681.727219749.00683.761359779.61483.60432 9789.9282.971179800.22677.01178
9810.53373.655929831.61376.104699842.18373.936339873.99476.551749918.36775.30183
9965.76176.564249989.93961.27569   1000160.6476410006.9561.2547110015.3165.82413
10024.0872.3693110039.9478.77863 10051.8 79.639510162.1678.7367110172.6180.47718
10234.4581.4808410254.7183.9397910405.52 86.054710525.6184.7843810570.3683.09423
#Mann= 3 , 0 , 0
9429.625   0.075       09429.625   0.075       010570.36   0.075       0
#XS Ineff= 2 , 0
       0                               0
Bank Sta=9429.625,10570.36
Exp/Cntr=0.3,0.1

Type RM Length L Ch R = 1 ,8486.913,249.511000,249.511000,249.511000
XS GIS Cut Line= 6
927791.319852625816199.652817917927788.688019808816004.817435097
927796.099700284815567.382776229927810.438176675815297.498692876
927806.845348556815193.521608529 927793.15586637815056.824073463
#Sta/Elev= 30
9427.898110.17149442.552107.17779482.556106.44779522.559102.73039842.657 84.8203
9872.67584.105519912.69984.916949972.70671.882179982.70664.918699992.70656.51257
10002.7154.1168910012.7156.7322510022.71  63.84910042.7170.5907210102.7675.15039
10112.7774.0847610122.7975.1991810142.8471.9007610192.9772.2085610223.0573.76832
 10243.172.2717510263.1272.6357210283.1375.2896410303.1381.0698410323.1485.53059
10333.1487.0016410353.1687.7766110483.4585.29816 10533.785.3403310572.0783.75155
#Mann= 3 , 0 , 0
9427.898   0.075       09427.898   0.075       010572.07   0.075       0
#XS Ineff= 2 , 0
       0                               0
Bank Sta=9427.898,10572.07
Exp/Cntr=0.3,0.1

Type RM Length L Ch R = 1 ,8237.402,249.510900,249.510900,249.510900
XS GIS Cut Line= 6
928130.989304047816191.904824332928060.269744571815744.589996744
928040.784345622815567.554231029928029.273303973815495.227764899
928002.088907834815377.686407734927917.412650007815061.595998695
#Sta/Elev= 30
9423.915120.72789461.225120.47719511.773110.30419531.993104.85719552.212101.7803
9612.93396.985629643.33196.668349714.25991.222039754.78989.884719805.45386.22639
 9835.8582.119299896.554 80.97689916.72478.757579957.05573.281249967.09668.84534
9977.13766.334759987.17856.596559997.219 49.802610007.2651.7808810027.3664.47028
10047.4567.1628810118.2769.2432410179.5269.7377910195.3768.6014910230.9972.55703
10241.2976.7914110272.3282.1619110313.7385.67954 10386.287.7748610576.0784.37467
#Mann= 3 , 0 , 0
9423.915   0.075       09423.915   0.075       010576.07   0.075       0
#XS Ineff= 2 , 0
       0                               0
Bank Sta=9423.915,10576.07
Exp/Cntr=0.3,0.1

Type RM Length L Ch R = 1 ,7987.891,249.510900,249.510900,249.510900
XS GIS Cut Line= 6
 928548.33624443816035.105550011 928502.34697856815892.778632437
928432.281089261815746.108192116928122.400550549815334.191685545
928054.706573114815208.157920635927986.482669341 815033.28152398
#Sta/Elev= 30
9420.261104.10799451.554100.17889472.344104.72749493.38998.53758 9525.1794.89717
9578.364 90.95779677.45486.762049688.72483.645999757.31481.753769905.24380.75995
9952.968 78.90629968.35873.715619994.42949.93195   1000148.5967810007.58 48.9511
10020.8557.8280310034.1262.3065210099.7562.7008810112.6765.1036210125.5963.01555
10138.1463.2282910172.7567.55314 10223.966.1261210259.4368.4211510283.8770.89018
10350.8784.8275510503.4386.0903310524.7285.28673   1054681.4152210579.7683.84884
#Mann= 3 , 0 , 0
9420.261  0.0721       09420.261  0.0721       010579.76  0.0721       0
#XS Ineff= 2 , 0
       0                               0
Bank Sta=9420.261,10579.76
Exp/Cntr=0.3,0.1

Type RM Length L Ch R = 1 , 7738.38,249.510900,249.510900,249.510900
XS GIS Cut Line= 6
928749.309459209815784.161360648928621.219726025815506.064275659
928522.581322244815399.613514813928245.481378578815185.416439169
928152.624268113815045.926956409928078.061110335814871.352166261
#Sta/Elev= 30
9418.52778.328349438.485 79.50139480.34378.737199490.92579.638519501.50682.33901
9512.08881.189319599.53978.865929767.88778.489189813.45176.933479834.16975.04482
9906.48874.055349919.04672.171119947.26164.619349966.11160.906389984.96250.70476
10002.4947.82206   1002656.5009710037.7658.69814 10109.557.9521610166.0759.72878
10182.9164.0235410210.4267.8537410249.2376.1917510299.2479.9672110403.5981.21988
 10425.876.6287610436.9179.4890710448.0179.5848310459.1281.2741110581.4576.97525
#Mann= 3 , 0 , 0
9418.527  0.0588       09418.527  0.0588       010581.45  0.0588       0
#XS Ineff= 2 , 0
       0                               0
Bank Sta=9418.527,10581.45
Exp/Cntr=0.3,0.1

Type RM Length L Ch R = 1 ,7488.869,249.511000,249.511000,249.511000
XS GIS Cut Line= 6
928805.605370458815709.088528554928770.748484882 815570.07828525
 928734.22752104815467.199578884928487.272467536814900.776551978
928437.831699773 814748.25499997928404.868641295814616.402855789
#Sta/Elev= 30
9416.56376.029859523.74578.713369596.814 78.5447 9607.4477.709899639.44977.49593
9660.78978.424699682.38376.660389725.89876.981139813.73773.963479862.77269.31584
9923.95159.873649939.66658.702229956.88354.904929967.81953.463099978.75648.13027
10000.61 44.447610011.52 45.963410022.4451.7397110044.29 56.590210087.9758.06823
10120.7360.75057   1013360.3643910175.02 61.920410196.7464.0582710207.53 63.2848
10239.7268.1475210261.1769.5466510387.9870.5740110492.1169.2694410583.4370.01258
#Mann= 3 , 0 , 0
9416.563   0.075       09416.563   0.075       010583.43   0.075       0
#XS Ineff= 2 , 0
       0                               0
Bank Sta=9416.563,10583.43
Exp/Cntr=0.3,0.1

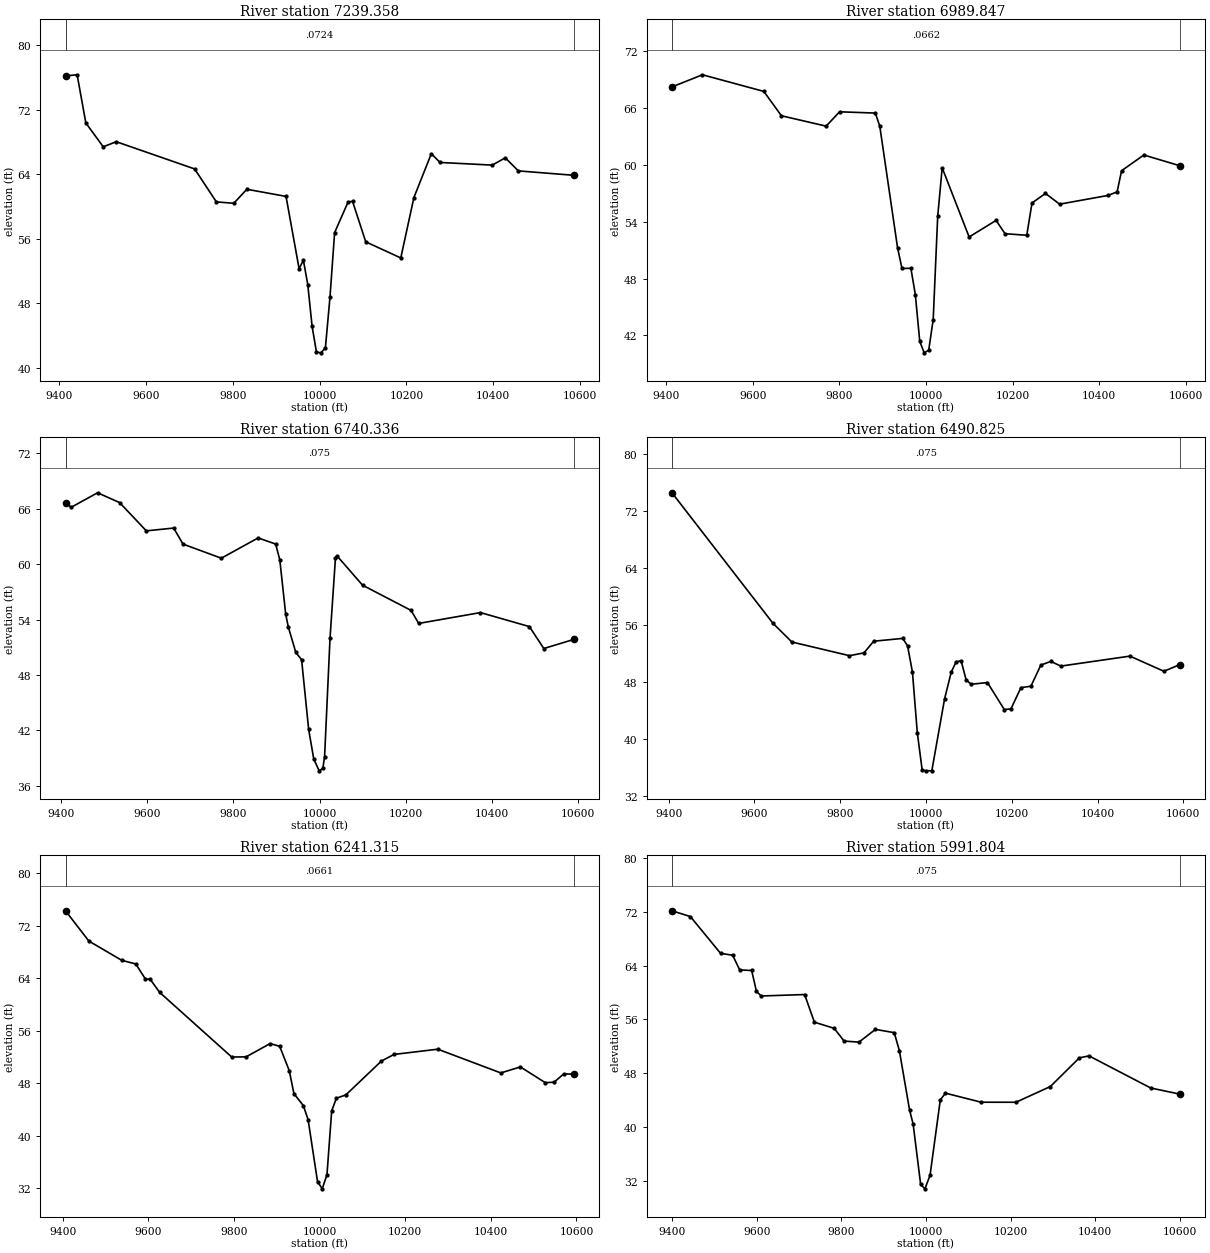
Type RM Length L Ch R = 1 ,7239.358,249.510900,249.510900,249.510900
XS GIS Cut Line= 6
928876.869195056815691.740335752928840.928019587815111.422762705
928818.803803981815033.053543506928802.567170044814915.511503654
928788.186605866814736.838774903928780.101984661814527.885024478
#Sta/Elev= 30
9414.87176.217569441.66276.358429461.69970.379499501.77467.42235 9531.8368.05053
9712.22964.674429762.38160.582859802.50260.407749832.59362.14915 9922.8461.26239
9952.86752.305199962.86853.327229972.86850.327949982.868 45.14419992.86841.95192
10002.9841.8477810013.5242.4669710024.1248.7964210034.7256.7621410065.7860.57167
10076.0460.6503810106.4555.6245810187.1653.6268110217.3261.1090910257.4866.56451
10277.5665.4767510397.8565.1480410427.8866.0510810457.9264.42912 10585.163.88497
#Mann= 3 , 0 , 0
9414.871  0.0724       09414.871  0.0724       0 10585.1  0.0724       0
#XS Ineff= 2 , 0
       0                10059.58       0
Bank Sta=9414.871,10585.1
Exp/Cntr=0.3,0.1

Type RM Length L Ch R = 1 ,6989.847,249.510900,249.510900,249.510900
XS GIS Cut Line= 6
928937.627544383815684.958566823928953.807000922815539.486329957
 928974.05819096815432.204598379929052.074699115815116.373227667
 929155.98506139814736.782436765929202.054902034814543.770026447
#Sta/Elev= 30
9413.55368.199189483.843   69.489625.57167.727729666.27865.159729769.484 64.0639
9800.45865.576549883.05665.444519893.31564.063279934.34251.252359944.59949.05971
9965.113 49.08419975.36946.317319985.62641.37278  9995.9  40.16910006.2940.45339
10016.66 43.677110027.02 54.548110037.39 59.6736 10099.652.38134 10161.854.12882
10182.5352.7261910232.68 52.562810244.7455.9640810275.8456.9737210308.4955.84063
10420.7156.7649610441.2757.1394710451.5559.3676710502.95 61.022810586.47 59.8871
#Mann= 3 , 0 , 0
9413.553  0.0662       09413.553  0.0662       010586.47  0.0662       0
#XS Ineff= 2 , 0
       0                10039.74       0
Bank Sta=9413.553,10586.47
Exp/Cntr=0.3,0.1

Type RM Length L Ch R = 1 ,6740.336,249.511000,249.511000,249.511000
XS GIS Cut Line= 6
928986.499032012815768.252238677929025.144629137815583.601220499
929092.572395003815423.801637679929164.725750181815328.012527135
929395.126763381815109.758062764929580.213154212814782.741782511
#Sta/Elev= 30
9411.13366.640589424.58766.176229485.50167.740789536.58466.67586 9598.4763.61595
9661.96663.916899683.41362.182499772.38460.650419857.70962.84981 9898.3462.18373
 9907.9560.469619921.60954.570249927.70253.19163 9945.0750.434319958.42649.65167
9974.77442.111149986.56138.902619999.19937.6100110007.5837.8688910011.7539.13701
10024.3251.97061 10036.960.6409910040.3660.9140210099.74 57.727910212.29 54.9926
10229.9153.5833410373.0354.7592610486.5553.2407110519.9550.8655810588.8951.84241
#Mann= 3 , 0 , 0
9411.133   0.075       09411.133   0.075       010588.89   0.075       0
#XS Ineff= 2 , 0
       0                10066.68       0
Bank Sta=9411.133,10588.89
Exp/Cntr=0.3,0.1

Type RM Length L Ch R = 1 ,6490.825,249.510900,249.510900,249.510900
XS GIS Cut Line= 6
929188.546163846815954.687361492929239.378284766815811.156155506
929318.936792263  815637.3255975929465.762904515815358.503767729
929637.076427026815068.900380333929726.110194368814901.498143631
#Sta/Elev= 30
 9407.6374.612799642.79256.298429687.16653.64484 9821.5551.720099855.43852.11558
 9878.0353.752879945.80654.151279957.10253.091999968.39849.406919979.69440.92359
9990.98935.70158    999935.5387410013.6235.5573710043.3345.6489810058.91 49.4206
10070.3450.8674510081.9651.0030810093.5748.3272810105.1947.7037810143.3347.94562
10182.6144.1482610198.1444.2477810221.38 47.227910244.6247.4268110267.8550.39926
10291.0950.9200410314.3350.2559810475.5651.6594610554.7549.5305810592.3750.47637
#Mann= 3 , 0 , 0
 9407.63   0.075       0 9407.63   0.075       010592.37   0.075       0
#XS Ineff= 2 , 0
       0                10072.14       0
Bank Sta=9407.63,10592.37
Exp/Cntr=0.3,0.1

Type RM Length L Ch R = 1 ,6241.315,249.510900,249.510900,249.510900
XS GIS Cut Line= 6
929404.241903112816055.016979167929483.409975185815879.041717885
929628.036104854815593.372758627929695.211603508815448.299836462
929857.508150702815145.631037466 929935.13955309814994.628477735
#Sta/Elev= 30
9406.858 74.24779461.38969.637339538.00366.711549571.15666.138839593.25963.86305
9604.37363.83262 9626.7961.817659794.91851.981029828.54452.003829884.58654.02438
9907.00453.609589929.25949.908879940.27446.401059962.30444.568949973.31942.44824
9995.34833.0043710006.3531.9073510017.3834.07483 10028.443.7848910039.4345.70624
10061.4946.2127810144.3151.3533710173.8652.3747810276.16 53.170110423.35 49.5552
10469.0450.4708210527.2248.0752410547.7548.1487710570.2449.4038510593.1449.36885
#Mann= 3 , 0 , 0
9406.858  0.0661       09406.858  0.0661       010593.14  0.0661       0
#XS Ineff= 2 , 0
       0                10105.53       0
Bank Sta=9406.858,10593.14
Exp/Cntr=0.3,0.1

Type RM Length L Ch R = 1 ,5991.804,249.510900,249.510900,249.510900
XS GIS Cut Line= 6
929575.801321055816174.553385016929645.281274274816029.573772823
929724.583532624815883.247542388930006.346213865815446.557061362
930094.360579709815288.477226559 930171.75407077 815133.00413795
#Sta/Elev= 30
9399.15572.153139442.71571.291469514.04665.825559542.73965.53989  9559.363.35626
9587.68463.270689598.97660.152239610.26759.478569712.931 59.69189736.03755.58141
9782.85654.666789806.26552.77397 9841.3852.612729880.43654.509919924.96554.02139
9937.04551.335889961.20542.49185 9969.5640.434849987.38531.439159997.446 30.7906
10009.5932.8094610033.8444.0224810045.9745.0237910130.3943.67757 10212.743.67074
10294.1846.0093510362.8850.2798910385.6350.5677410531.5945.7906310600.8444.87592
#Mann= 3 , 0 , 0
9399.155   0.075       09399.155   0.075       010600.84   0.075       0
#XS Ineff= 2 , 0
       0                10060.13       0
Bank Sta=9399.155,10600.84
Exp/Cntr=0.3,0.1

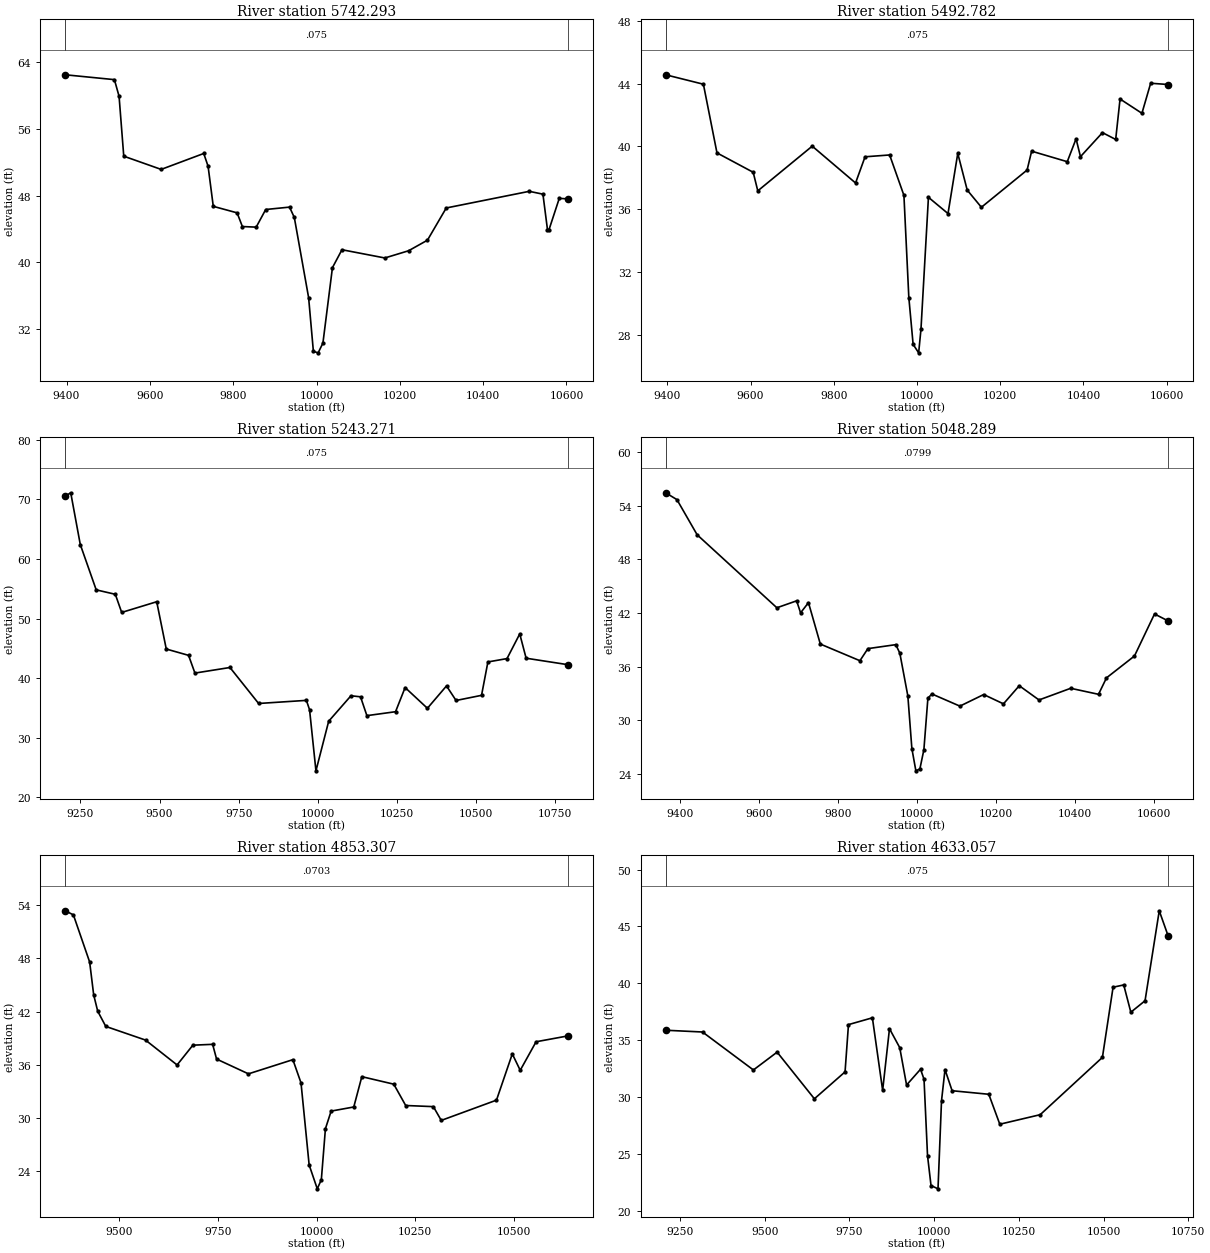
Type RM Length L Ch R = 1 ,5742.293,249.511000,249.511000,249.511000
XS GIS Cut Line= 6
929800.435679561816321.846007589 929851.07427576816213.986751863
929920.668343747816077.621531788930225.339219379 815525.47979284
930284.560691085815405.420506554930353.281175334815250.456527006
#Sta/Elev= 30
9396.86162.464069514.89761.881549526.10659.885619537.33352.715899627.14951.13154
9729.324 53.03969739.75651.507899752.20846.707769809.419 45.92999822.06244.28879
9855.18744.218139878.07146.329789935.28246.616239946.72445.37636 9981.05 35.7787
9992.49229.3393310003.95 29.164810015.3830.3344910038.2439.36865 10061.141.51229
10163.98 40.526110220.8741.3872910266.2642.6546410311.43  46.51410510.6548.50666
10543.4748.1658510554.4143.9063110558.0443.9107710582.7147.6652310603.1447.60147
#Mann= 3 , 0 , 0
9396.861   0.075       09396.861   0.075       010603.14   0.075       0
#XS Ineff= 2 , 0
       0                 10057.7       0
Bank Sta=9396.861,10603.14
Exp/Cntr=0.3,0.1

Type RM Length L Ch R = 1 ,5492.782,249.510900,249.510900,249.510900
XS GIS Cut Line= 6
930031.011464292816448.339305116930187.651590014816101.362039137
930350.730971721815826.406327487930400.508405976815729.161430922
930459.662814582815582.649414382930535.786019575815354.847254843
#Sta/Elev= 30
9395.95644.561389486.656   43.969519.30539.585969606.37338.352259617.40637.16868
9748.30240.016149852.437   37.679875.24939.338369934.33739.454839968.69136.88239
9980.49530.376169990.80827.3926810004.1126.8539610009.6628.3509310027.6336.75835
10074.6835.7232910098.1439.5542110120.8637.2167910154.9336.1240510264.8138.49443
10275.6739.6962210361.34 39.026610382.5240.48426 10393.139.3465310445.9940.87701
10477.7340.4433710488.2543.0186210540.8142.1091210561.8444.0218310604.0543.94193
#Mann= 3 , 0 , 0
9395.956   0.075       09395.956   0.075       010604.05   0.075       0
#XS Ineff= 2 , 0
       09908.208        10054.68       0
Bank Sta=9395.956,10604.05
Exp/Cntr=0.3,0.1

Type RM Length L Ch R = 1 ,5243.271,194.981700,194.981700,194.981700
XS GIS Cut Line= 2
930434.623189932 816812.26840606930606.498189932 815234.14340606
#Sta/Elev= 30
9201.94670.563049219.31771.123569249.49462.43375 9299.7954.816549360.14554.07353
9380.263 51.02589490.91452.823219521.09144.879229591.50543.818589611.62340.83989
9722.27441.777959812.80635.734419963.69336.256229973.75234.67623 9993.8724.42079
10034.1132.7526210104.5237.02906 10134.736.8549810154.8233.6905610245.3534.35246
10275.5338.4097710345.9434.9284710406.2938.6826510436.4736.2370510516.9537.10268
10537.0642.7101110597.4243.2747610637.6547.4211910657.7743.33662 10789.442.25434
#Mann= 3 , 0 , 0
9201.946   0.075       09201.946   0.075       0 10789.4   0.075       0
#XS Ineff= 2 , 0
       09929.916        10101.62       0
Bank Sta=9201.946,10789.4
Exp/Cntr=0.3,0.1

Type RM Length L Ch R = 1 ,5048.289,194.981600,194.981600,194.981600
XS GIS Cut Line= 6
930699.303016556816642.704683657930744.282266536816339.777453034
930738.036372132816164.747818952930689.160073679  815787.8046421
930700.918711971815582.913808402930733.537794671815380.841916774
#Sta/Elev= 30
 9363.6455.432249392.17554.66745 9443.3550.74015 9645.2642.58537  9695.343.36074
  9705.342.01826  9725.343.157869755.30738.531689855.58736.668929875.75638.02044
9946.48838.464559956.64837.513099976.96632.726429987.12626.861539997.28524.36652
10007.4424.5794810017.5826.7297310027.7332.4837710037.8732.9545110108.7731.59608
10169.0432.8910910219.0931.8504810259.1133.8757710309.1232.2854310389.3733.58915
 10459.8 32.916210479.9834.7520110550.8737.1971310601.6641.8921610636.3641.11098
#Mann= 3 , 0 , 0
 9363.64  0.0799       0 9363.64  0.0799       010636.36  0.0799       0
#XS Ineff= 2 , 0
       09914.662        10147.06       0
Bank Sta=9363.64,10636.36
Exp/Cntr=0.3,0.1

Type RM Length L Ch R = 1 ,4853.307,220.250200,220.250200,220.250200
XS GIS Cut Line= 6
930921.929031594816595.013874403930953.861374586816444.806771936
930961.324934141816292.050854541930858.591657864815723.576732041
930856.257759618815542.666520149 930881.18444291815335.553407704
#Sta/Elev= 30
9362.38353.370589383.089 52.90929424.35347.593839434.57343.893459444.79342.05442
9465.23440.339749566.07238.799019646.19935.99434 9686.2538.223139736.39738.31778
9746.42636.657589827.31234.991849940.02536.590679960.66533.974099981.30624.72538
10001.9522.0321510012.2723.07141 10022.6 28.807110037.13 30.794110094.5531.25751
10114.9834.6752110196.06  33.82810226.2831.4247410296.5131.2971710316.5429.74411
10456.6732.0287810496.8137.23768 10516.935.3911410557.19 38.608810637.6239.26566
#Mann= 3 , 0 , 0
9362.383  0.0703       09362.383  0.0703       010637.62  0.0703       0
#XS Ineff= 2 , 0
       09905.606        10149.46       0
Bank Sta=9362.383,10637.62
Exp/Cntr=0.3,0.1

Type RM Length L Ch R = 1 ,4633.057,104.578500,104.578500,104.578500
XS GIS Cut Line= 6
931178.546801043816703.761461616931170.449160814816234.583271965
931137.848170757815992.113408476931107.284742624815871.897257671
930939.798845018815470.532558213 930876.46346771815269.733683838
#Sta/Elev= 30
9207.38635.891259316.15435.73637 9466.3932.403059536.39333.968559646.39929.87303
9736.93632.235289747.026 36.38469817.65636.982779847.92630.612119868.10636.02563
9898.37634.363719918.55631.081289959.76332.467549970.081  31.5869980.39924.87955
9990.71722.2592110011.3521.9682510021.6729.6836810031.9932.4386110052.9830.58132
10161.2630.2700410193.7827.64055   1031328.47746 10496.733.5093410528.1639.66894
10559.6239.8684610580.5937.4719410622.5338.4791410664.4746.3784110690.9744.15255
#Mann= 3 , 0 , 0
9207.386   0.075       09207.386   0.075       010690.97   0.075       0
#XS Ineff= 2 , 0
       09940.963        10085.67       0
Bank Sta=9207.386,10690.97
Exp/Cntr=0.3,0.1

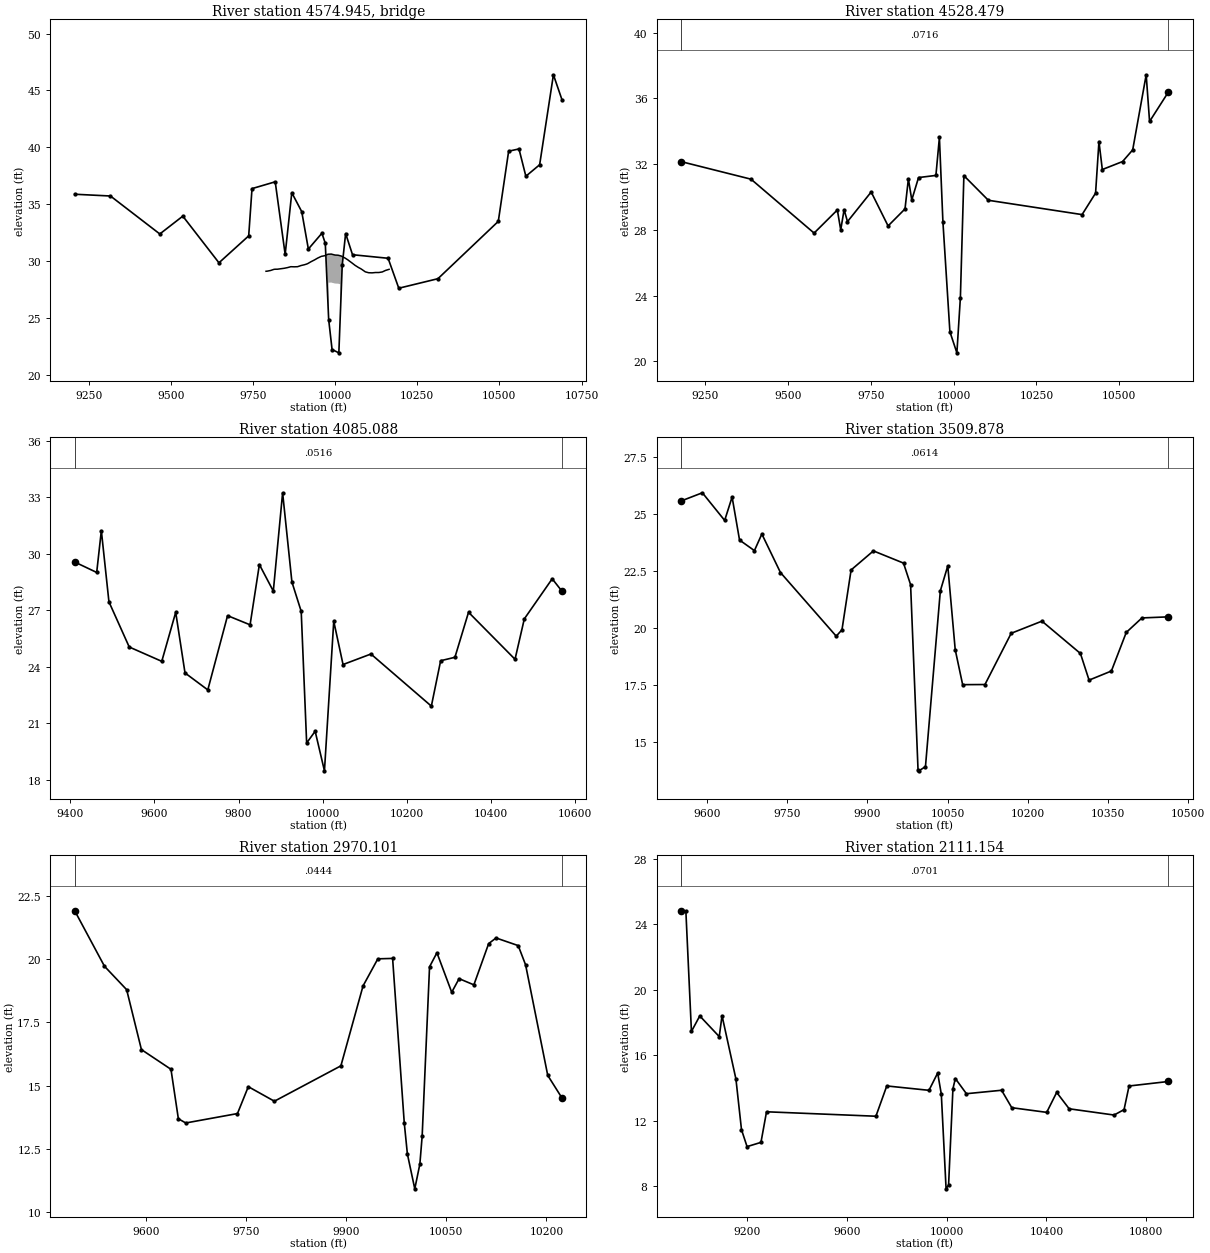
Type RM Length L Ch R = 3 ,4574.945,,,
BEGIN DESCRIPTION:
END DESCRIPTION:
Bridge Culvert--1,0,-1,-1, 0
Deck Dist Width WeirC Skew NumUp NumDn MinLoCord MaxHiCord MaxSubmerge Is_Ogee
31.294250,41.990000,2.6,0, 52, 52, , , 0.95, 0, 0,0,,
 9789.69 9793.57 9803.81 9814.05 9819.15 9824.29 9834.53 9844.77 9855.01 9865.25
 9865.58 9875.49 9885.73 9895.97 9906.21 9912.00 9916.45 9926.69 9936.93 9947.17
 9957.41 9958.42 9967.66 9977.90 9980.17 9980.17 9983.12 9988.19 9998.5510001.04
10008.9110015.6010015.6010019.2710029.6310039.3310039.9910050.3510060.7110071.07
10077.6210081.4310091.7910102.1510112.5110115.9210122.8710133.2310143.5910153.95
10154.2110164.28
   29.13   29.14   29.20   29.30   29.31   29.31   29.35   29.39   29.45   29.53
   29.53   29.52   29.53   29.63   29.70   29.75   29.80   29.97   30.12   30.29
   30.43   30.44   30.49   30.62   30.63   30.63   30.63   30.64   30.56   30.55
   30.54   30.49   30.49   30.46   30.30   30.12   30.10   29.88   29.65   29.46
   29.36   29.29   29.08   29.00   28.99   29.00   29.02   29.02   29.07   29.21
   29.21   29.30
 -970.87 -970.86 -970.80 -970.70 -970.69 -970.69 -970.65 -970.61 -970.55 -970.47
 -970.47 -970.48 -970.47 -970.37 -970.30 -970.25 -970.20 -970.03 -969.88 -969.71
 -969.57 -969.56 -969.51 -969.38 -969.37   28.13   28.13   28.14   28.06   28.05
   28.04   27.99 -969.51 -969.54 -969.70 -969.88 -969.90 -970.12 -970.35 -970.54
 -970.64 -970.71 -970.92 -971.00 -971.01 -971.00 -970.98 -970.98 -970.93 -970.79
 -970.79 -970.70
 9789.69 9793.57 9803.81 9814.05 9819.15 9824.29 9834.53 9844.77 9855.01 9865.25
 9865.58 9875.49 9885.73 9895.97 9906.21 9912.00 9916.45 9926.69 9936.93 9947.17
 9957.41 9958.42 9967.66 9977.90 9980.89 9980.89 9983.12 9988.19 9998.5510001.04
10008.9110016.3210016.3210019.2710029.6310039.3310039.9910050.3510060.7110071.07
10077.6210081.4310091.7910102.1510112.5110115.9210122.8710133.2310143.5910153.95
10154.2110164.28
   29.13   29.14   29.20   29.30   29.31   29.31   29.35   29.39   29.45   29.53
   29.53   29.52   29.53   29.63   29.70   29.75   29.80   29.97   30.12   30.29
   30.43   30.44   30.49   30.62   30.63   30.63   30.63   30.64   30.56   30.55
   30.54   30.48   30.48   30.46   30.30   30.12   30.10   29.88   29.65   29.46
   29.36   29.29   29.08   29.00   28.99   29.00   29.02   29.02   29.07   29.21
   29.21   29.30
 -970.87 -970.86 -970.80 -970.70 -970.69 -970.69 -970.65 -970.61 -970.55 -970.47
 -970.47 -970.48 -970.47 -970.37 -970.30 -970.25 -970.20 -970.03 -969.88 -969.71
 -969.57 -969.56 -969.51 -969.38 -969.37   28.13   28.13   28.14   28.06   28.05
   28.04   27.98 -969.52 -969.54 -969.70 -969.88 -969.90 -970.12 -970.35 -970.54
 -970.64 -970.71 -970.92 -971.00 -971.01 -971.00 -970.98 -970.98 -970.93 -970.79
 -970.79 -970.70
BR Coef=-1 , 0 , 0 ,, 0 ,,,0.8,0,1,0,
WSPro=,,,, 1 ,,,, 0 ,,,, 0 ,,,,-1 ,-1 ,-1 , 0 , 0 , 0 , 0 , 0
BC Design=,, 0 ,, 0 ,,,,,,

Type RM Length L Ch R = 1 ,4528.479,443.390600,443.390600,443.390600
XS GIS Cut Line= 6
931309.531882352816706.441549444931303.546801043816235.011461616
 931251.46346771815985.011461616931175.074578821815759.317017171
 931159.92306367815538.537796392931105.630134377815259.317017171
#Sta/Elev= 30
9176.99832.156519388.577 31.08519578.96727.807219649.14129.213139659.35628.00099
 9669.5729.231599679.78528.504729751.28830.306289802.36228.241849853.43529.27701
 9863.6531.100719873.865 29.82319894.29431.184049946.73831.314299957.29533.62099
9967.85328.506529988.96721.8065810010.0820.5234610020.6423.88467 10031.231.30017
 10105.129.8019710388.0528.9312210428.7930.2369810438.9833.3744410449.1731.67247
10510.2932.1579410540.85 32.8673 10581.637.4353910591.7934.5945210648.5236.38273
#Mann= 3 , 0 , 0
9176.998  0.0716       09176.998  0.0716       010648.52  0.0716       0
#XS Ineff= 2 , 0
       09925.709        10053.77       0
Bank Sta=9176.998,10648.52
Exp/Cntr=0.3,0.1

Type RM Length L Ch R = 1 ,4085.088,575.210200,575.210200,575.210200
XS GIS Cut Line= 2
931370.387078821 816562.26840606931863.442634377815513.657294949
#Sta/Elev= 30
9410.46929.561749462.70229.007839473.75231.225659491.81427.448829540.054 25.0509
9617.40624.290349650.556 26.89299672.65723.674299726.82722.774669773.82926.71536
9827.36126.228729849.46129.426159882.61228.017839904.71333.236619926.81328.50086
9948.91426.94149 9961.8419.954469982.065 20.579610004.17 18.478310026.2726.41749
10048.3724.1206910114.6724.6788410258.3221.9128410280.42 24.322910314.3624.50482
10346.7226.8946410457.2324.3993210479.3326.5438610545.6328.6706710569.2128.00157
#Mann= 3 , 0 , 0
9410.469  0.0516       09410.469  0.0516       010569.21  0.0516       0
#XS Ineff= 2 , 0
       09869.234                       0
Bank Sta=9410.469,10569.21
Exp/Cntr=0.3,0.1

Type RM Length L Ch R = 1 ,3509.878,539.776900,539.776900,539.776900
XS GIS Cut Line= 2
931516.220412154816864.351739393932171.602356599816230.671183838
#Sta/Elev= 30
9551.20725.57526 9591.24 25.93729632.96924.725539646.87925.750889660.78923.86491
9688.60923.401589702.51924.129279737.29722.442089841.61919.651669852.38819.93191
9869.43922.553989911.16923.389299967.47822.854749980.71921.908219994.629 13.8011
9996.25113.7484610008.5413.9324310036.3621.6382310050.2722.7320710064.1819.06057
10078.0917.5258510119.8217.5319610168.8919.7779710226.4320.3100210298.3618.89353
10314.5617.7247410356.2918.1238510384.1119.8153110413.4520.4514110462.84  20.498
#Mann= 3 , 0 , 0
9551.207  0.0614       09551.207  0.0614       010462.84  0.0614       0
#XS Ineff= 2 , 0
       09926.887                       0
Bank Sta=9551.207,10462.84
Exp/Cntr=0.3,0.1

Type RM Length L Ch R = 1 ,2970.101,858.947400,858.947400,858.947400
XS GIS Cut Line= 2
931624.727356599817246.296183838932284.449578821816933.796183838
#Sta/Elev= 30
9493.48921.923949538.05119.726459571.24718.799589593.37716.425949637.63815.64553
9648.70313.687129659.768 13.51959737.22413.892249753.47414.95732 9792.5514.38102
9892.13615.782639925.33218.949119947.46220.020729969.59220.036989987.07213.51348
9991.72312.2917310002.7910.9110110010.4311.8951310013.8512.9972210024.9219.70536
10035.9820.2617210058.1118.6961910069.1819.2353310091.3118.9901710113.4420.62258
 10124.520.84762 10157.7 20.544810168.7719.7827910201.9615.4033610223.48 14.4999
#Mann= 3 , 0 , 0
9493.489  0.0444       09493.489  0.0444       010223.48  0.0444       0
#XS Ineff= 2 , 0
       0 9941.78                       0
Bank Sta=9493.489,10223.48
Exp/Cntr=0.3,0.1

Type RM Length L Ch R = 1 ,2111.154,102.727300,102.727300,102.727300
XS GIS Cut Line= 6
931387.318335498818454.950864661931783.380665332818259.095866391
932254.935689932817813.136461616932296.602356599817750.636461616
932334.796801043817615.219794949932305.018963997816967.499318979
#Sta/Elev= 30
8934.25224.836828953.97824.811988976.28917.452439009.757 18.40229087.84817.13692
9099.00418.415839154.78314.541789177.09511.441839199.40710.405059255.18610.66449
9277.49812.536789716.27112.264629759.86614.117969929.089 13.85019964.04614.90915
9978.63713.612089997.7527.82156510007.828.06265710025.2413.9485310034.91 14.5719
10079.3313.6426610220.39 13.854210261.1912.7875110401.38 12.501610441.4313.72323
10491.4712.7200210671.6512.3375910711.6812.67029 10731.7  14.11510889.3514.39054
#Mann= 3 , 0 , 0
8934.252  0.0701       08934.252  0.0701       010889.35  0.0701       0
#XS Ineff= 2 , 0
       0                10042.41       0
Bank Sta=8934.252,10889.35
Exp/Cntr=0.3,0.1