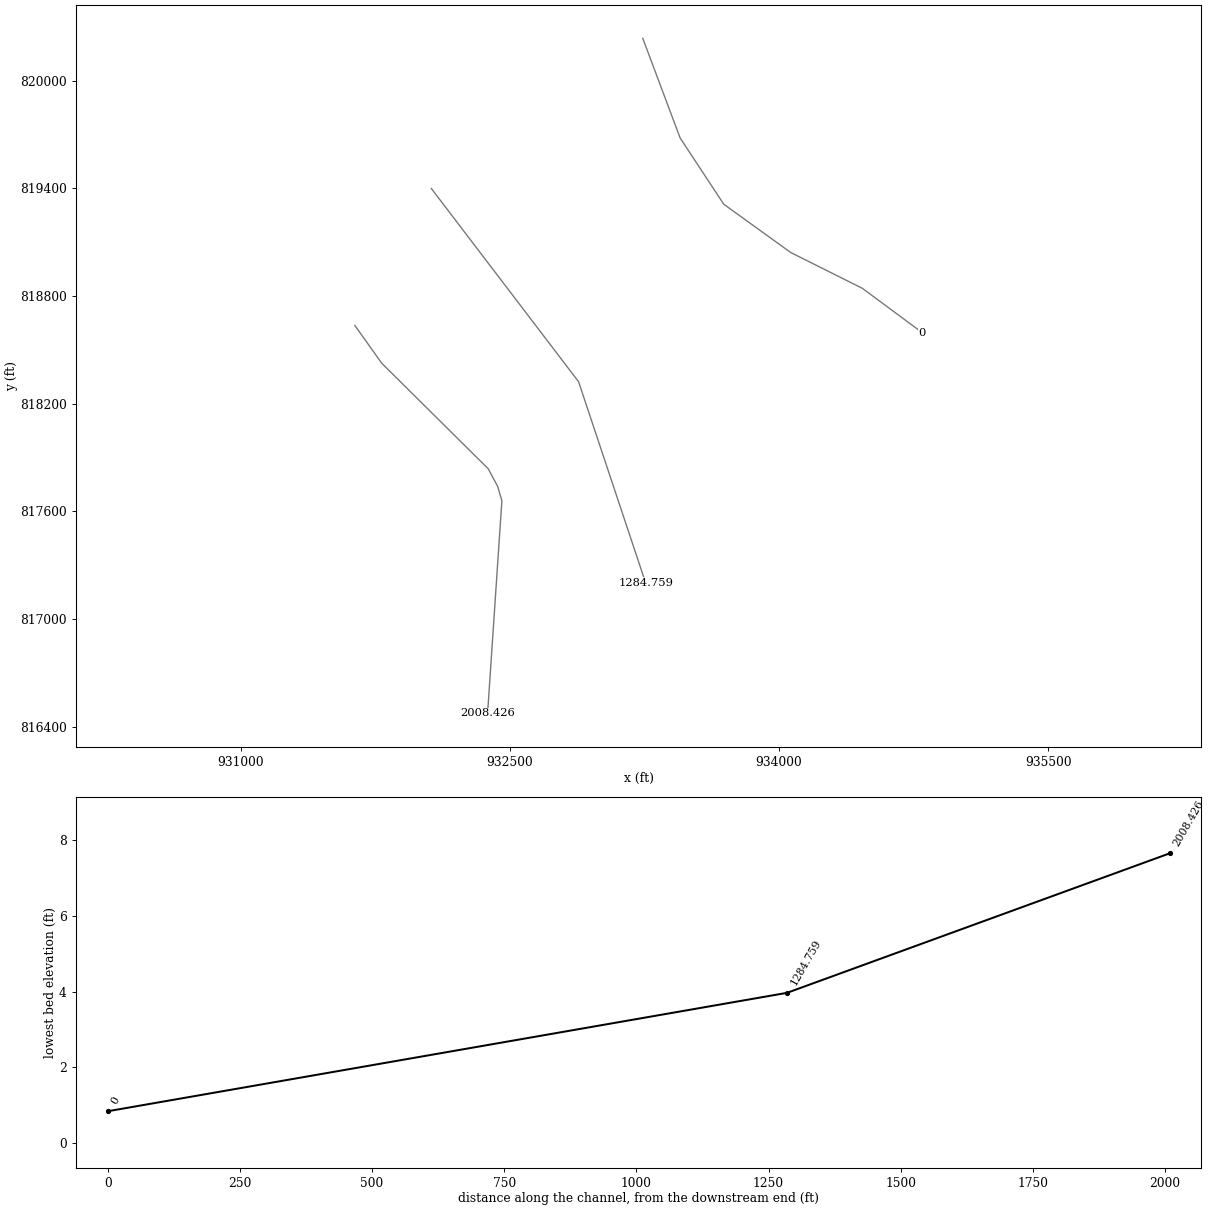
HEC-RAS study 15896_ras.prj: 15896

--- 15896_ras.g01 (geometry) --- (continued)

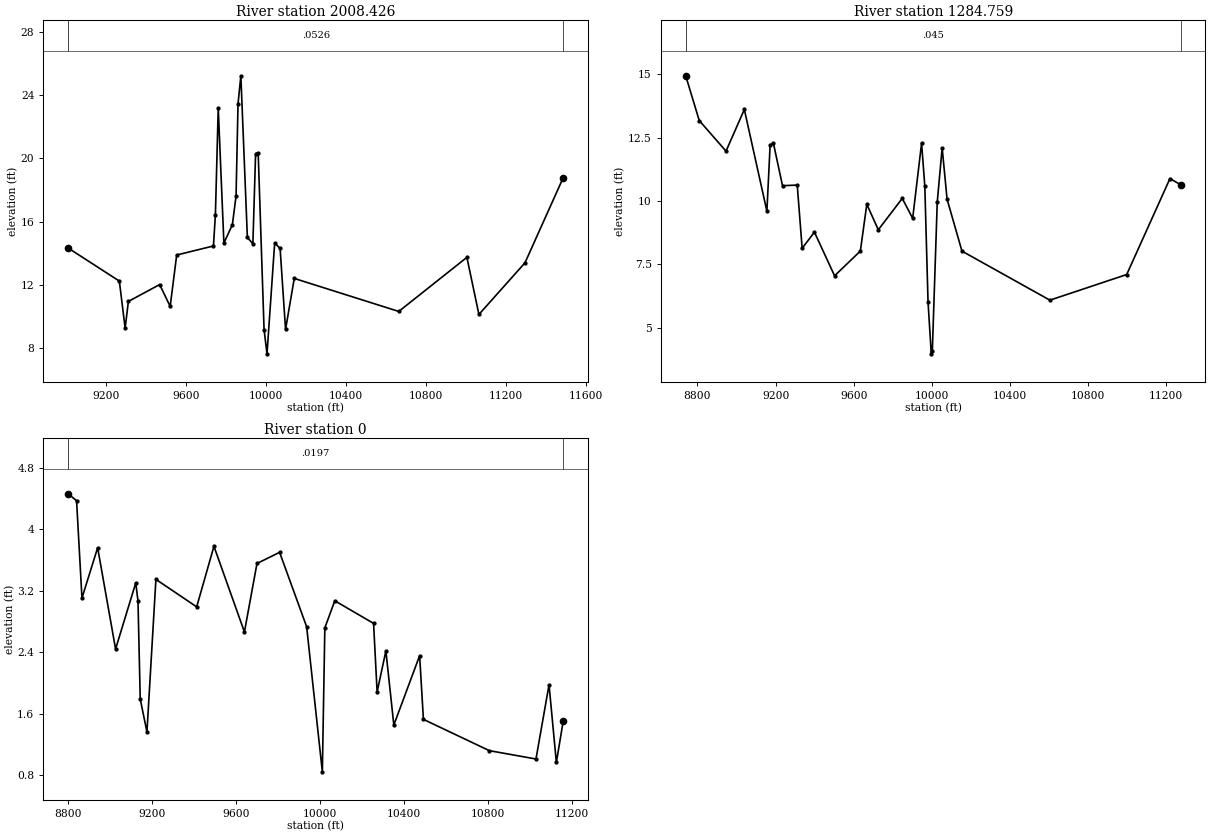
Type RM Length L Ch R = 1 ,2008.426,723.667400,723.667400,723.667400
XS GIS Cut Line= 6
931636.880134377818636.053128282931785.679066761 818426.63240863
932379.935689932817837.442017171932432.019023265817740.219794949
932455.946908782817659.735089122932376.278746899816474.616230065
#Sta/Elev= 30
9009.67114.33026  9265.412.245439294.3899.2714599310.543 10.96089467.15112.02656
9519.68910.645139552.27113.891679736.11914.464079745.96416.441049760.10623.17775
 9788.3914.646769830.816 15.80259849.25617.623019859.10123.436599873.24325.21063
9905.82515.003939933.38414.600349947.00620.293059959.90320.345489989.3569.182805
10004.087.65152110042.3614.64266 10069.614.3146810096.859.19342110140.3812.41347
10663.1210.3287511003.9813.7434811064.1410.1378911294.7713.4029311485.6818.77202
#Mann= 3 , 0 , 0
9009.671  0.0526       09009.671  0.0526       011485.68  0.0526       0
#XS Ineff= 2 , 0
       0                10047.09       0
Bank Sta=9009.671,11485.68
Exp/Cntr=0.3,0.1

Type RM Length L Ch R = 1 ,1284.759,1284.759000,1284.759000,1284.759000
XS GIS Cut Line= 3
932063.095412154819399.073961616932883.407912154818322.685072727
933256.671801043 817202.89340606
#Sta/Elev= 30
8740.053 14.94358809.18713.178138946.34311.969089040.15613.614159155.6419.598826
9172.13912.205019188.63712.29551 9235.5210.605359310.958 10.62969336.1048.135087
9398.9698.7725639502.0967.0487939634.0798.0264119667.0749.8725859725.866 8.86536
9848.55110.103849901.887 9.317289947.53812.284229964.03610.582079980.5346.016052
9997.0313.96945110002.474.07176410027.629.94868410052.7612.1013210077.9110.07453
 10154.28.02290810604.396.08794510997.477.09908311218.8310.8850111273.7610.64355
#Mann= 3 , 0 , 0
8740.053   0.045       08740.053   0.045       011273.76   0.045       0
#XS Ineff= 2 , 0
       0                10061.82       0
Bank Sta=8740.053,11273.76
Exp/Cntr=0.3,0.1

Type RM Length L Ch R = 1 ,       0,0.000000,0.000000,0.000000
XS GIS Cut Line= 6
933241.025452354820236.299353652933449.358785688819680.743798096
933692.414341243819311.820186985934065.678230132819042.722964763
934464.983785688818843.070186985934799.185174576818595.674353652
#Sta/Elev= 30
8799.2854.4614988839.085 4.371058864.7533.1051768939.5133.7598969024.9532.441667
9121.0733.3015749131.7533.0675189142.4331.7915579174.4731.3625729217.193 3.34787
9411.4722.9902369493.7553.778611    96392.6639849698.8763.5545629806.6533.699852
9935.5072.731848 10010.4 0.8438510022.272.71726610069.723.06937310254.522.775153
10271.391.88324210313.19 2.4168110351.071.45271510474.05 2.3553710492.081.526423
10806.351.11943211028.54 1.0108611090.751.97657711125.690.96561311158.171.502294
#Mann= 3 , 0 , 0
8799.285  0.0197       08799.285  0.0197       011158.17  0.0197       0
#XS Ineff= 2 , 0
       0                               0
Bank Sta=8799.285,11158.17
Exp/Cntr=0.3,0.1